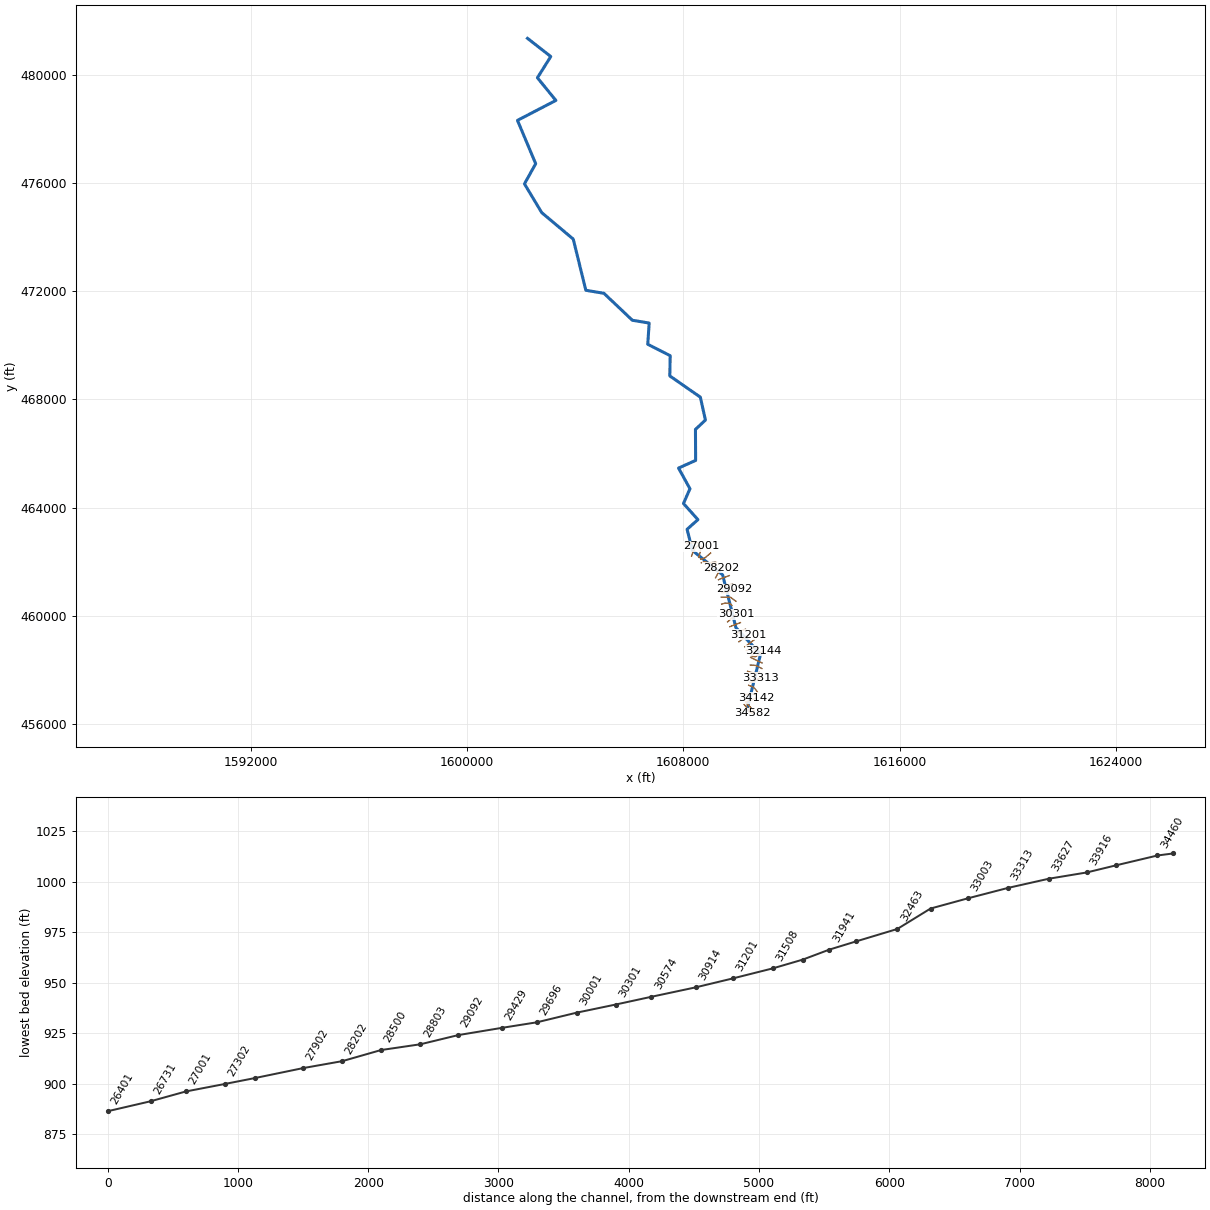
--- LngRn.prj (project) ---

Proj Title=LngRn
Current Plan=p01
Default Exp/Contr=0,0
English Units
Geom File=g01
Flow File=f01
Plan File=p01
BEGIN DESCRIPTION:
---------- MODELED AS PART OF WVEM CTP PROGRAM, 2025----------
Stream Name: Long Run
Flood Zone: AFH
Marshall County, WV
HEC-RAS Version: RAS 6.6
Vertical Datum: NAVD88
Projection: NAD 1983 StatePlane West Virginia N FIPS 4701 (US Feet)
Terrain: 1-meter West Virginia FEMA R3 South Central (collected 2018-2019)
Land Use: 2024 NLCD
Hydrologic Method:
Duda et al., "Estimation of magnitude and frequency of floods for rural, unregulated streams in and near Virginia and West Virginia." September 8, 2025.
Additional Model Notes:
None
END DESCRIPTION:
DSS File=dss
DSS Export Rating Curves= 0
DSS Export Rating Curve Sorted= 0
DSS Export Volume Flow Curves= 0
DXF OffsetX= 0
DXF OffsetY= 0
DXF ScaleX= 0
DXF ScaleY= 0

--- LngRn.p01 (plan) ---

Plan Title=Floodplain
Program Version=6.60
Short Identifier=Floodplain
Geom File=g01
Flow File=f01
Subcritical Flow
K Sum by GR= 0
Std Step Tol= 0.01
Critical Tol= 0.01
Num of Std Step Trials= 20
Max Error Tol= 0.3
Flow Tol Ratio= 0.001
Split Flow NTrial= 30
Split Flow Tol= 0.02
Split Flow Ratio= 0.02
Log Output Level= 0
Friction Slope Method= 1
Unsteady Friction Slope Method= 2
Unsteady Bridges Friction Slope Method= 1
Parabolic Critical Depth
Global Vel Dist= 0 , 0 , 0
Global Log Level= 0
CheckData=False
Encroach Param=-1 ,0,0, 0
Flow Ratio Tolerance=0.1
Flow Ratio Min Ratio=0.5
Flow Ratio Max Ratio=4
Flow Ratio Max Iterations= 10
Computation Interval=0.1SEC
Output Interval=1SEC
Instantaneous Interval=Max Profile
Mapping Interval=1HOUR
Computation Time Step Use Courant=        0
Computation Time Step Use Time Series=    0
Computation Time Step Count To Double=0
Computation Time Step Max Doubling=0
Computation Time Step Max Halving=0
Computation Time Step Residence Courant=0
Run HTab= 0
Run UNet= 0
Run Sediment= 0
Run PostProcess= 0
Run WQNet= 0
Run RASMapper=-1
UNET Theta= 0
UNET Theta Warmup= 0
UNET ZTol= 0
UNET ZSATol= 0
UNET MxIter= 0
UNET Max Iter WO Improvement= 0
UNET MaxInSteps= 0
UNET DtIC= 0
UNET DtMin= 0
UNET MaxCRTS= 0
UNET WFStab= 0
UNET SFStab= 0
UNET WFX= 1
UNET SFX= 1
UNET Gravity=32.17405
UNET 1D Methodology=Finite Difference
UNET DSS MLevel= 1
UNET Pardiso=0
UNET DZMax Abort= 0
UNET Use Existing IB Tables= 0
UNET Froude Reduction=False
UNET Froude Limit= 0
UNET Froude Power= 0
UNET D1 Cores= 0
UNET WindReference=Eulerian
UNET WindDragFormulation=Hsu (1988)
UNET D2 Coriolis=0
UNET D2 Cores= 0
UNET D2 Theta= 1
UNET D2 Theta Warmup= 1
UNET D2 Z Tol= 0.01
UNET D2 Volume Tol= 0.01
UNET D2 Max Iterations= 20
UNET D2 Advanced Convergence=0
UNET D2 WS Max Tol=0.15
UNET D2 WS RMS Tol=0.002
UNET D2 WS Stall Tol=1
UNET D2 Equation= 0
UNET D2 RampUpFraction=0.1
UNET D2 TimeSlices= 1
UNET D2 Turbulence Formulation=Non-Conservative (original)
UNET D2 Eddy Viscosity=0.3
UNET D2 Transverse Eddy Viscosity=0.1
UNET D2 Smagorinsky Mixing=0
UNET D2 BCVolumeCheck=0
UNET D2 Cores=0
UNET D2 SolverType=PARDISO (Direct)
UNET D2 Minimum Iterations= 3
UNET D2 Maximum Iterations= 30
UNET D2 Restart Number= 10
UNET D2 Relaxation Coeff=1.3
UNET D2 SOR Precondition Iterations= 10
UNET D2 ILUT Maximum Fill= 8
UNET D2 ILUT Tolerance=1E-08
UNET D2 Convergence Tolerance=0.00001
PS Theta= 1
PS WS Tol= 0.01
PS Volume Tol= 0.01
PS Max Iterations= 20
PS Equation= 0
PS Advance Time Step=-1
PS Target Courant=0.9
PS Time Slices= 1
PS Iterate With 2D=0
PS Project Initial WSE from DS=-1
PS Ramp Up Initial WSE from US=-1
PS Cores=0
UNET D1D2 MaxIter= 0
UNET D1D2 ZTol=0.01
UNET D1D2 QTol=0.1
UNET D1D2 MinQTol=1
DSS File=dss
Write IC File= 0
Write IC File at Fixed DateTime=0
Write IC File at Sim End=0
Echo Input=False
Echo Parameters=False
Echo Output=False
Write Detailed= 0
HDF Write Warmup=0
HDF Write Time Slices=0
HDF Flush=0
HDF Compression= 1
HDF Chunk Size= 1
HDF Spatial Parts= 1
HDF Use Max Rows=0
HDF Fixed Rows= 1
Calibration Method= 0
Calibration Iterations= 20
Calibration Max Change=0.05
Calibration Tolerance=0.2
Calibration Maximum=1.5
Calibration Minimum=0.5
Calibration Optimization Method= 1
WQ AD Non Conservative
WQ ULTIMATE=-1
WQ Max Comp Step=1HOUR
WQ Output Interval=15MIN
WQ Output Selected Increments= 0
WQ Create Restart=0
WQ Fixed Restart=0
WQ System Summary=0
WQ Write To DSS=0
Sorting and Armoring Iterations= 10
XS Update Threshold= 0.02
Bed Roughness Predictor= 0
Processes Affected by Predictor=Sediment Only
Hydraulics Update Threshold= 0.02
Energy Slope Method= 1
Volume Change Method= 1
Sediment Retention Method= 0
Sediment TS Multiplier= 1
Warm Up Method= 0
XS Weighting Method= 0
Number of US Weighted Cross Sections= 1
Number of DS Weighted Cross Sections= 1
Upstream XS Weight=0
Main XS Weight=1
Downstream XS Weight=0
Number of DS XS's Weighted with US Boundary= 1
Upstream Boundary Weight= 1
Weight of XSs Associated with US Boundary= 0
Number of US XS's Weighted with DS Boundary= 1
Downstream Boundary Weight= 0.5
Weight of XSs Associated with DS Boundary= 0.5
Percentile Method= 0
Sediment Output Level= 3
Mass or Volume Output= 0
Output Increment Type= 1
Profile and TS Output Increment= 1
Transport Output Increment 1
XS Output Flag= 0
XS Output Increment= 10
Read HDF5 Sediment Hotstart= 0
Sediment Hotstart Type= 0
Write Gradation File= 0
Read Gradation Hotstart= 0
Write HDF5 File= 1
Write Binary Output= 1
Write DSS Sediment File= 0
DSS Sediment Output Type= 1
SV Curve= 0
Specific Gage Flag= 0
Subcell Erosion Methods= 0
Subcell Deposition Methods= 0
Advection Scheme= 1
Matrix Solver= 0
Implicit Weighting Factor= 1
Maximum Outer Loop Convergence Iterations= 5
Convergence Maximum Absolute= 0.001
Convergence RMSE= 0.0001
Grain Fractions Max Abs Error= 0.001
Max Subgrid Regions= 1
Max Subgrid Length Scale= 3.402823E+38
Initial Layer Thickness= 3
Min Layer Thickness= 0.1
Max Layer Thickness= 6
Number of Layers= 5

--- LngRn.f01 (steady flow) ---

Flow Title=Flow
Program Version=6.60
Number of Profiles= 1
Profile Names=P100yr
River Rch & RM=LngRn,Main,34582
     783
River Rch & RM=LngRn,Main,32144
     967
River Rch & RM=LngRn,Main,29429
    1100
River Rch & RM=LngRn,Main,26731
    1530
River Rch & RM=LngRn,Main,23674
    1750
River Rch & RM=LngRn,Main,19773
    2010
River Rch & RM=LngRn,Main,14536
    2240
River Rch & RM=LngRn,Main,9889
    2560
Boundary for River Rch & Prof#=LngRn,Main            , 1
Up Type= 0
Dn Type= 3
Dn Slope=0.009123
DSS Import GetInterval= 0
DSS Import GetPeak= 0
DSS Import FillOption= 0

--- LngRn.g01 (geometry) ---

Geom Title=Geometry
Program Version=6.60

River Reach=LngRn           ,Main
Reach XY= 30
     1610352.281      456523.3721610852.81654684458582.431478048
     1609944.553      459560.722     1609451.521      461515.988
     1608338.101       462414.64 1608137.7613921      463199.143
     1608538.479      463556.041     1608004.405      464153.397
     1608243.774      464698.563     1607822.805      465463.169
     1608453.915      465746.105     1608447.423      466890.964
     1608816.069      467238.135     1608628.172      468085.207
     1607498.967      468870.195     1607513.284      469618.223
     1606683.889      470040.5561606735.77651495470824.649486661
     1606114.761      470928.315     1605062.375      471925.647
      1604394.81      472036.812     1603928.835      473929.224
     1602763.845      474908.103     1602124.979        475969.3
     1602540.152      476717.399     1601867.285      478318.966
      1603286.39      479056.256      1602604.83      479894.042
     1603097.714      480679.729      1602237.72      481352.236

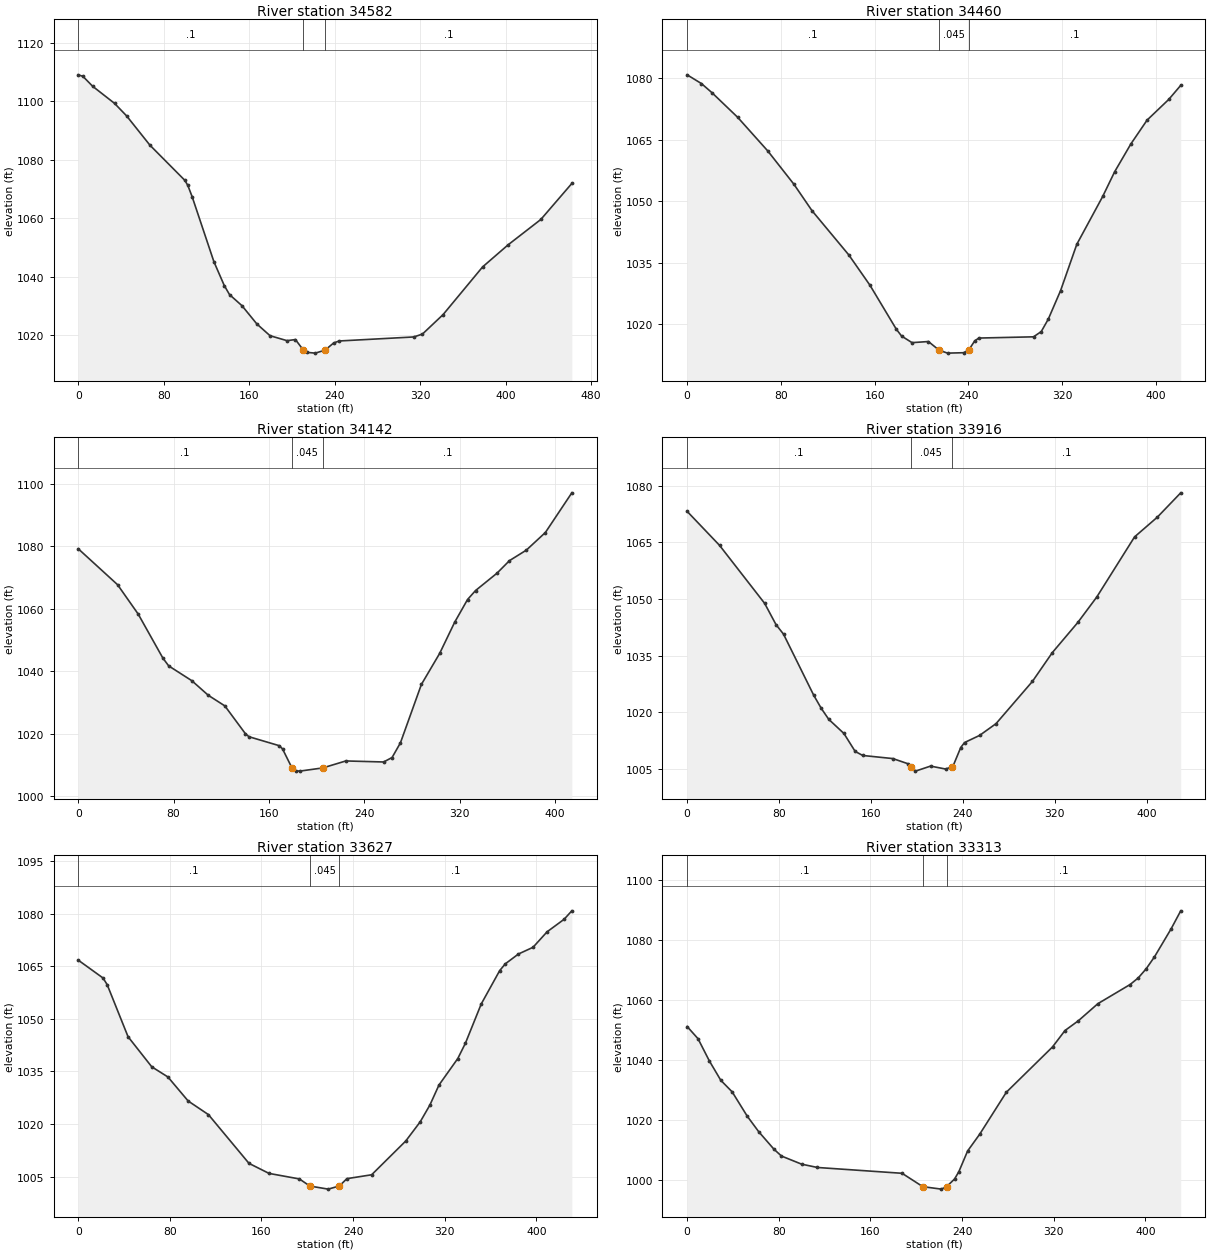
Type RM Length L Ch R = 1 ,34582   ,119.3,122.5,124.7
XS GIS Cut Line= 4
1610246.23583074456723.108309857  1610368.598384456577.104316751
 1610423.8592089 456473.486882481610555.36430771456393.203484973
#Sta/Elev= 30
       0 1109.03     4.4 1108.51    13.5 1105.12      34 1099.27    45.3 1094.99
    67.1 1084.99    99.7    1073   102.5  1071.3   106.6  1067.4     127 1045.15
   136.7 1037.01   141.6 1033.92   153.3 1030.11   167.2 1023.88   179.5 1019.87
   195.4 1018.17   203.3 1018.55   210.7 1014.96   214.4 1014.16   221.9 1013.91
   231.11014.948     239 1017.36   244.2 1018.06   314.1 1019.44   322.2 1020.43
   341.5 1027.08   378.5 1043.38   402.4 1050.94     433  1059.6     462  1071.9
#Mann= 3 ,-1,0
       0      .1       0   210.7    .045       0   231.1      .1       0
Bank Sta=210.7,231.1
XS Rating Curve= 0 ,0
Exp/Cntr=0.3,0.1

Type RM Length L Ch R = 1 ,34460   ,296.3,317.3,328.2
XS GIS Cut Line= 4
1610322.19839159 456772.465579491610465.80239937456637.959978723
1610524.49058951456570.5749046211610620.49377289456475.501863135
#Sta/Elev= 30
       0 1080.82    12.2 1078.69    21.2 1076.46    43.1 1070.46    68.9 1062.21
    91.1 1054.12   106.6 1047.64     138 1036.84     156 1029.46   178.5 1018.72
     183 1017.05   191.9 1015.44   205.9 1015.71     215  1013.6   222.2 1012.88
   235.9 1012.98   240.2 1013.59   245.4 1015.87   248.9 1016.56   295.6 1016.86
   302.2 1018.15   308.2 1021.19   318.7 1028.16   332.5 1039.44   354.6 1051.12
   364.8 1057.15   378.7 1063.97   392.5 1069.77     411 1074.82   421.2 1078.25
#Mann= 3 ,-1,0
       0      .1       0     215    .045       0   240.2      .1       0
Bank Sta=215,240.2
XS Rating Curve= 0 ,0
Exp/Cntr(USF)=0,0
Exp/Cntr=0.3,0.1

Type RM Length L Ch R = 1 ,34142   ,233.1,226.6,222.7
XS GIS Cut Line= 3
1610309.69922852456819.056247495 1610456.0357089456868.422998875
1610698.00020488456962.554115403
#Sta/Elev= 30
       0 1079.23      33 1067.72    50.3 1058.32      71 1044.23    75.9 1041.72
    95.3 1036.98   109.1 1032.31     123 1028.91   140.3 1019.98   143.3 1019.03
   168.8 1016.15   171.4 1015.13   179.31009.052   182.3 1008.13   185.8 1008.02
   205.2 1009.05   224.5 1011.28   256.2 1010.95   263.3 1012.38   270.3 1017.07
   287.9 1035.79   303.2  1045.7   315.8 1055.69   326.6 1062.97   333.3 1065.84
   351.3  1071.4   361.8 1075.43   375.9 1078.78   391.9 1084.43   414.1 1097.14
#Mann= 3 ,-1,0
       0      .1       0   179.3    .045       0   205.2      .1       0
Bank Sta=179.3,205.2
XS Rating Curve= 0 ,0
Exp/Cntr(USF)=0,0
Exp/Cntr=0.3,0.1

Type RM Length L Ch R = 1 ,33916   ,300,288.6,278.3
XS GIS Cut Line= 6
1610266.84659159457099.5916760861610356.46977192457101.838062674
1610433.40596975457103.9391083421610533.90904959457101.890556008
1610608.70909683457096.4168136721610695.87230834457088.621225595
#Sta/Elev= 30
       0  1073.2    28.2 1064.21    67.5 1048.85    77.4 1043.22    83.9 1040.72
   110.2 1024.55   116.8 1021.06   123.3 1018.17   136.5 1014.43   146.3 1009.68
   152.9 1008.61   179.1 1007.79   192.2 1006.43   194.61005.634   198.8 1004.47
   211.9  1005.8   225.1 1005.02   230.51005.624   231.6 1005.89   238.2 1010.72
   241.5 1012.03   254.6 1013.92   268.9 1017.03   300.6 1028.21   317.9 1035.82
   340.1  1043.8   356.6 1050.53   389.5 1066.44   409.3 1071.65   429.7  1078.1
#Mann= 3 ,-1,0
       0      .1       0   194.6    .045       0   230.5      .1       0
Bank Sta=194.6,230.5
XS Rating Curve= 0 ,0
Exp/Cntr(USF)=0,0
Exp/Cntr=0.3,0.1

Type RM Length L Ch R = 1 ,33627   ,297.8,314,325.4
XS GIS Cut Line= 4
1610415.89803301 457432.298120071610570.40786031457370.113700788
1610648.90094559 457305.14408651  1610746.540186457175.154845178
#Sta/Elev= 30
       0 1066.81    21.7 1061.69    25.3 1059.79    43.5 1044.94    64.2 1036.34
    78.3 1033.44      96 1026.57   113.7 1022.68   149.1 1008.76   166.6 1005.89
   193.1 1004.31   202.31002.274   218.3  1001.4     2281002.303   234.6 1004.39
   256.2  1005.5     286 1015.15   298.6 1020.62   307.1 1025.44     315 1031.14
   331.4 1038.69   338.1 1043.09   351.9 1054.29     368 1063.81   372.9 1065.75
   384.4 1068.56   397.1 1070.47   409.4  1074.9   424.2 1078.46     431 1080.89
#Mann= 3 ,-1,0
       0      .1       0   202.3    .045       0     228      .1       0
Bank Sta=202.3,228
XS Rating Curve= 0 ,0
Exp/Cntr(USF)=0,0
Exp/Cntr=0.3,0.1

Type RM Length L Ch R = 1 ,33313   ,316.3,310.6,304.3
XS GIS Cut Line= 6
 1610462.7238245457540.108839676  1610554.194114457552.268592253
1610618.71629468457590.5030958351610704.74532209457641.483636916
1610772.21467534457674.7443971781610854.50092809 457706.73809959
#Sta/Elev= 30
       0 1051.08     9.5 1047.02    19.4 1039.61    29.4 1033.14    39.3 1029.29
    52.5 1021.16    62.5 1015.99    75.7  1010.2    82.3 1007.89    99.9 1005.18
   113.7 1004.07   187.6 1002.13   205.7997.6721   221.9  996.85   226.5997.6929
   233.4 1000.22   237.2 1002.71   244.8 1009.57   255.3 1015.14   278.6 1029.16
   318.9 1044.27   329.8 1049.75   341.4 1052.98   358.5  1058.7   386.6 1065.08
   393.7 1067.28   400.7 1070.36   407.8 1074.26   422.4 1083.65   430.8 1089.66
#Mann= 3 ,-1,0
       0      .1       0   205.7    .045       0   226.5      .1       0
Bank Sta=205.7,226.5
XS Rating Curve= 0 ,0
Exp/Cntr(USF)=0,0
Exp/Cntr=0.3,0.1

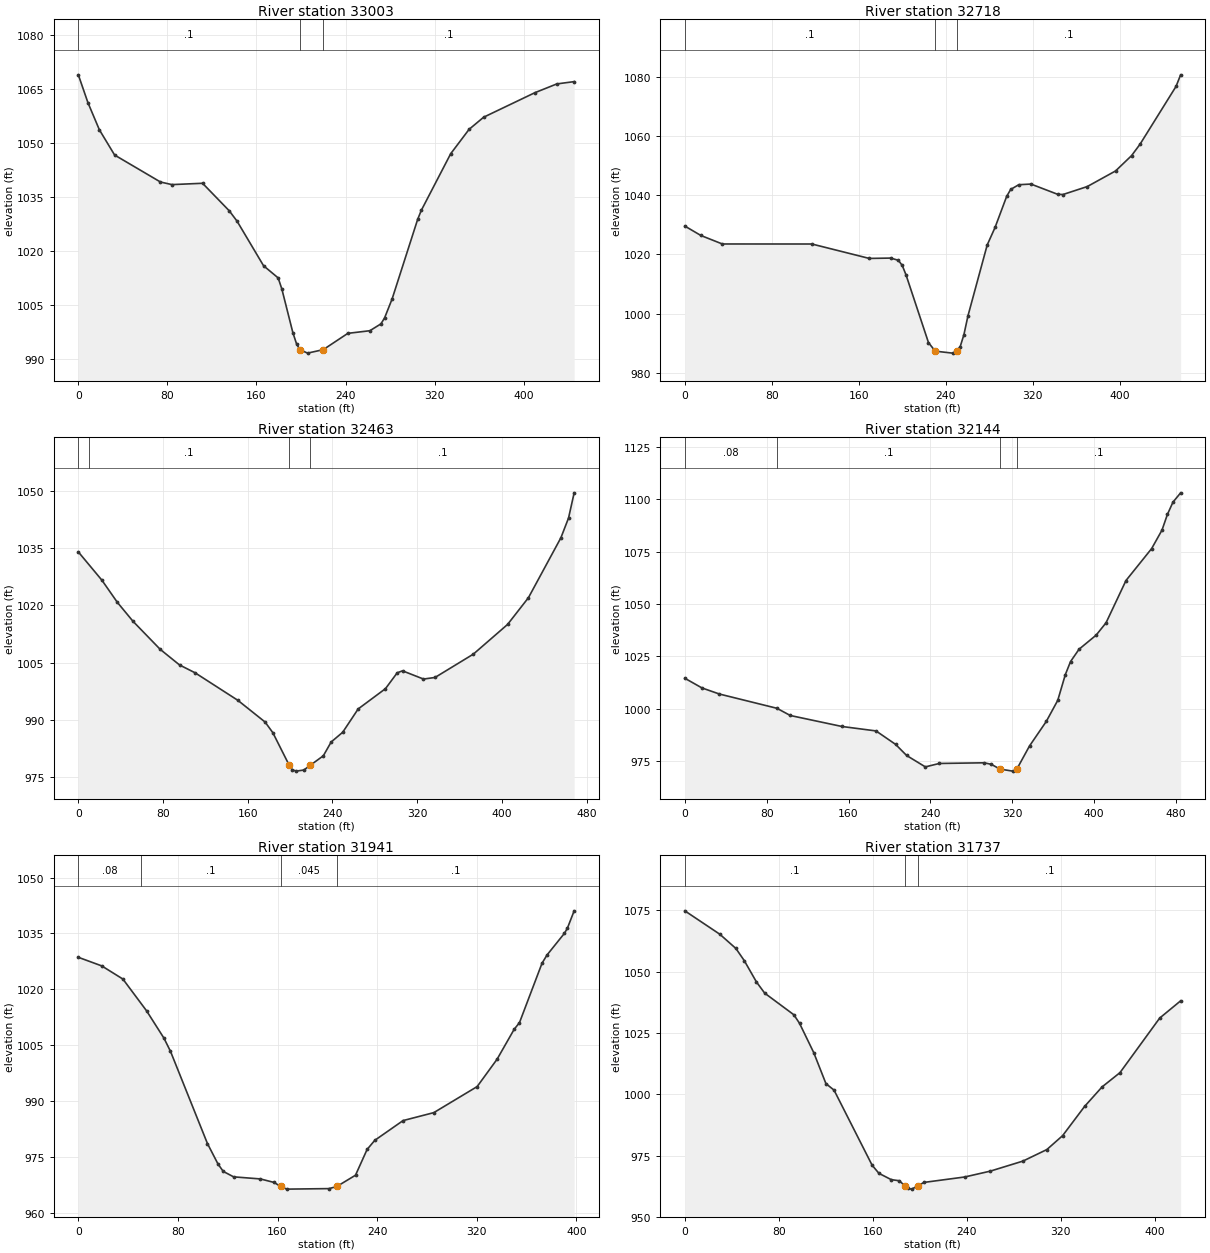
Type RM Length L Ch R = 1 ,33003   ,288.8,284.9,282.7
XS GIS Cut Line= 6
1610375.30667651 457949.561104761610459.02337259457924.104790837
1610530.65315059457901.8748484251610632.99677792457892.513646677
1610716.02548325457901.7554260941610812.50134018 457905.56709826
#Sta/Elev= 30
       0 1069.02     8.6  1061.3    18.9 1053.74    32.6 1046.72    73.8 1039.22
    84.1  1038.5   111.6 1038.87   135.6 1031.21   142.6 1028.33   166.4 1015.94
   179.5 1012.56   182.8  1009.5   192.7  997.36     196  994.25   198.9  992.64
   205.9  991.65     220992.6155   242.1  997.15   261.9  997.88   271.8  999.78
   275.1 1001.43   281.9 1006.74   304.8 1028.82   308.1 1031.35   334.5 1047.09
     351 1053.86   364.1 1057.24   410.1 1064.05   429.8 1066.49   445.4 1067.13
#Mann= 3 ,-1,0
       0      .1       0   198.9    .045       0     220      .1       0
Bank Sta=198.9,220
XS Rating Curve= 0 ,0
Exp/Cntr(USF)=0,0
Exp/Cntr=0.3,0.1

Type RM Length L Ch R = 1 ,32718   ,248.9,255.2,248.1
XS GIS Cut Line= 6
1610473.82485217 458182.219760181610574.78134318458174.664329082
1610664.02788384458165.6699245131610758.53064759458126.375055596
1610824.93537043458091.5119363371610902.40732834 458050.83846125
#Sta/Elev= 30
       0 1029.62    14.8 1026.42    34.5 1023.55   116.8 1023.54   169.6 1018.66
   189.3 1018.78   196.3 1018.03   199.9 1016.29   203.4 1013.06     224  990.19
   230.2  987.29   246.1  986.62   249.9 987.305   253.2  988.85   256.6  992.89
   260.3  999.23     278 1023.22   285.2 1029.13   295.9 1039.67   299.6 1042.01
     307  1043.6   318.2 1043.82   342.8 1040.35   347.7 1040.29     370 1042.98
     396 1048.26   410.7 1053.44   418.5 1057.31   451.6 1076.87   455.8 1080.78
#Mann= 3 ,-1,0
       0      .1       0   230.2    .045       0   249.9      .1       0
Bank Sta=230.2,249.9
XS Rating Curve= 0 ,0
Exp/Cntr(USF)=0,0
Exp/Cntr=0.3,0.1

Type RM Length L Ch R = 1 ,32463   ,308.6,318.4,326
XS GIS Cut Line= 3
1610488.37830076458462.3927562531610742.27754672458335.014629458
1610910.01403682458258.775881877
#Sta/Elev= 30
       0 1034.07    22.3 1026.63    36.9 1020.81    51.7 1015.83    77.3 1008.49
    95.6 1004.38   110.3 1002.32   150.7  995.09   176.4  989.39   183.7   986.6
   199.2978.0292   202.1  976.85   205.8   976.5     213  976.79   219.2978.0627
   231.4  980.53   238.8  984.15   249.7  986.71   264.3  992.83   290.1  998.16
   301.2 1002.33   306.2 1002.84     326 1000.68   336.9  1001.1   373.1 1007.23
   405.4 1015.02   425.1 1022.04   455.8  1037.8     463 1042.98   468.3 1049.59
#Mann= 4 ,-1,0
       0     .08       0      10      .1       0   199.2    .045       0
   219.2      .1       0
Bank Sta=199.2,219.2
XS Rating Curve= 0 ,0
Exp/Cntr(USF)=0,0
Exp/Cntr=0.3,0.1

Type RM Length L Ch R = 1 ,32144   ,209.4,203.6,200.7
XS GIS Cut Line= 4
1610556.56868208458499.3847812811610668.09939772458487.805700748
1610751.54557366458540.3832203421610966.86456999 458709.54514219
#Sta/Elev= 30
       0  1014.6    16.8 1009.97    33.9 1007.06      90 1000.28   103.1  996.84
   153.6   991.6   186.9  989.48     206  983.08   216.8  977.78   235.1  972.34
   248.7  973.97   292.5  974.29   299.5  973.58   308.1971.2789   320.5  970.32
   324.5  971.27   336.9   982.3   353.3  994.01   364.5 1004.05   371.9  1016.3
     377 1022.54   385.3 1028.41     402 1035.13   411.7 1041.02   431.2 1061.18
   456.3 1076.42   466.4 1085.22   471.7  1092.7   477.1 1098.52   484.6 1102.98
#Mann= 4 ,-1,0
       0     .08       0      90      .1       0   308.1    .045       0
   324.5      .1       0
Bank Sta=308.1,324.5
XS Rating Curve= 0 ,0
Exp/Cntr(USF)=0,0
Exp/Cntr=0.3,0.1

Type RM Length L Ch R = 1 ,31941   ,204.7,203.9,200.2
XS GIS Cut Line= 2
1610524.37645249458519.7984125141610777.23431513458827.418742626
#Sta/Elev= 30
       0 1028.59    18.8 1026.28    35.8 1022.74    54.8 1014.21    68.8 1006.84
      74 1003.33   103.7  978.53   112.2  973.02   116.4  971.05   124.7  969.59
   146.2  969.03   157.3  968.08   162.4967.0034   167.4  966.29   201.4  966.43
   207.7  967.02   222.6  970.03   231.9  976.95   238.1  979.41   260.8  984.71
   285.5  986.85   320.3  993.85   336.3  1001.2     350 1009.23   354.3 1011.04
   372.4    1027   376.4 1029.21   390.4 1035.04   392.8 1036.44   398.2 1041.08
#Mann= 4 ,-1,0
       0     .08       0      50      .1       0   162.4    .045       0
   207.7      .1       0
Bank Sta=162.4,207.7
XS Rating Curve= 0 ,0
Exp/Cntr(USF)=0,0
Exp/Cntr=0.3,0.1

Type RM Length L Ch R = 1 ,31737   ,222.8,228.6,231.2
XS GIS Cut Line= 3
1610329.19598487458717.0945239871610592.10308315458808.458708161
1610717.28648215458878.719979131
#Sta/Elev= 30
       0 1074.75    29.8 1065.21    43.5  1059.4    50.6 1054.46      61 1045.74
      68  1041.2    92.8 1032.39    97.6 1028.93   109.7 1016.98   120.1 1004.33
     127 1001.68   159.4  971.08   165.2  967.77   175.7   965.2   182.6  964.75
   187.2962.6829   189.6   961.6     193  961.34   198.4962.6637   203.4  964.07
   238.2  966.29     260  968.68   287.7  972.76   308.1  977.47   321.5  983.14
   340.2  995.05   355.1 1003.01   370.3 1008.81   404.1 1031.05   421.9 1038.07
#Mann= 3 ,-1,0
       0      .1       0   187.2    .045       0   198.4      .1       0
Bank Sta=187.2,198.4
XS Rating Curve= 0 ,0
Exp/Cntr(USF)=0,0
Exp/Cntr=0.3,0.1

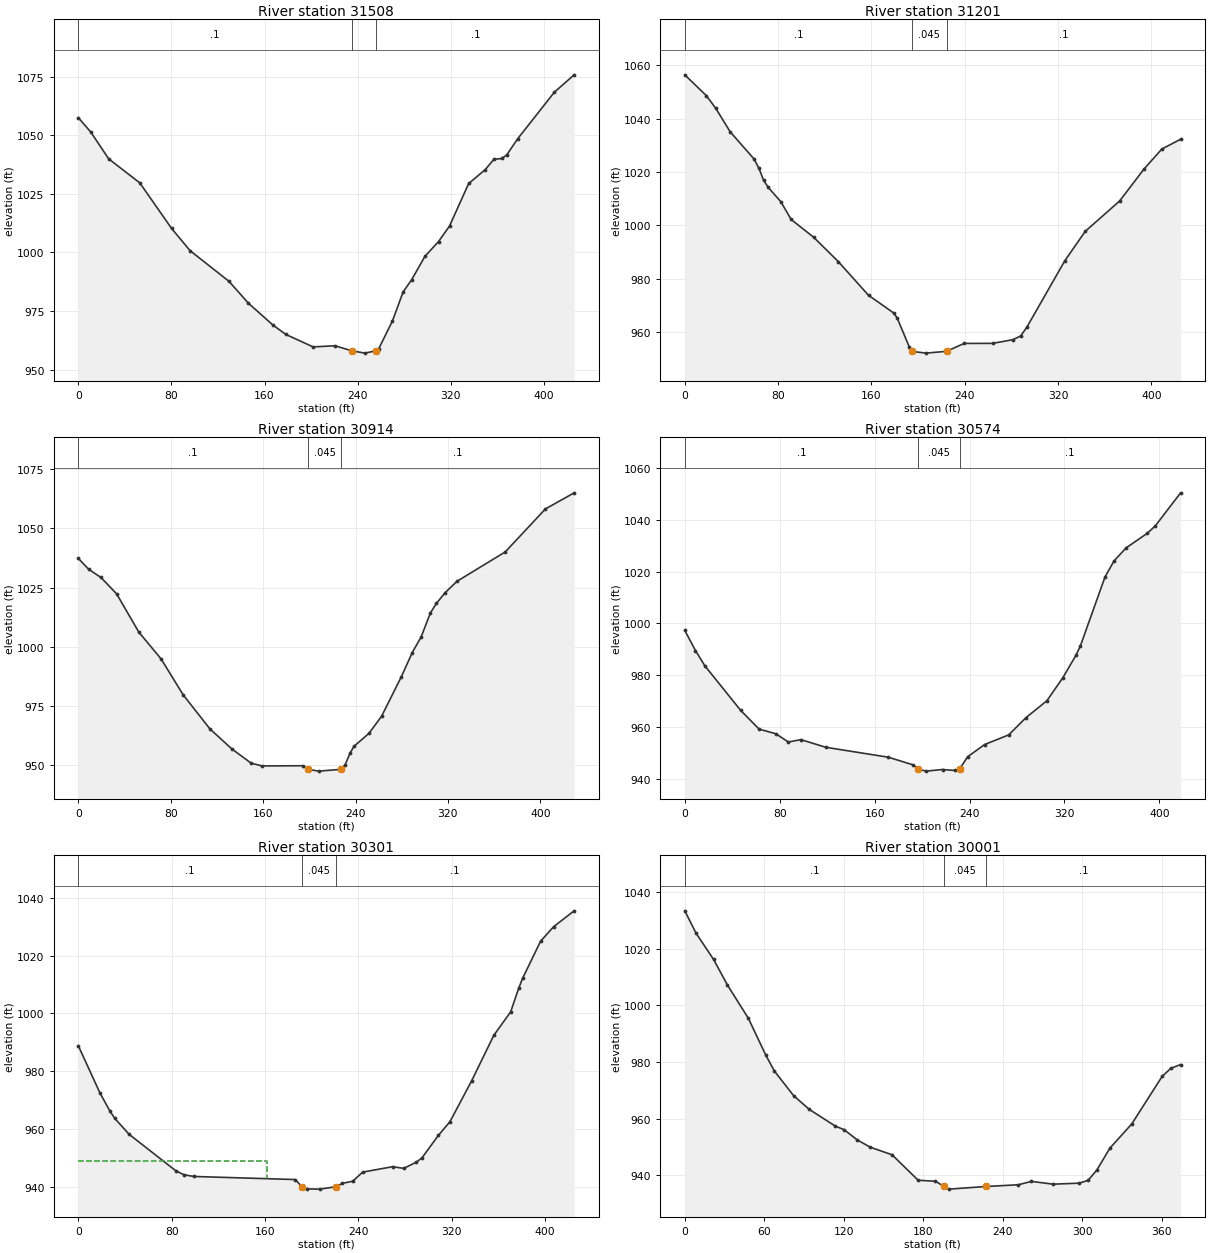
Type RM Length L Ch R = 1 ,31508   ,307.2,306.7,304.6
XS GIS Cut Line= 4
1610273.24388851458850.9224909991610353.99372701458909.899407178
1610423.91287851458965.2654381691610613.63566811459107.063200325
#Sta/Elev= 30
       0 1057.55    10.7 1051.43    26.1 1039.97    52.8 1029.73    80.1 1010.29
      96 1000.78   129.4  987.71   146.1  978.35     167  969.11   178.3  965.01
   201.7  959.69   220.5  960.17   234.8958.0523   246.2  957.03   256.1958.0775
     258  958.81   269.9  970.79   279.1  983.22   286.3   988.3   297.8  998.37
   309.5 1004.68   318.9 1011.29   335.4 1029.46   349.4 1035.29   357.1 1039.81
   364.1 1040.14   368.2 1041.76   377.5 1048.58   409.1  1068.5     426 1075.86
#Mann= 3 ,-1,0
       0      .1       0   234.8    .045       0   256.1      .1       0
Bank Sta=234.8,256.1
XS Rating Curve= 0 ,0
Exp/Cntr(USF)=0,0
Exp/Cntr=0.3,0.1

Type RM Length L Ch R = 1 ,31201   ,287.4,286.9,287.3
XS GIS Cut Line= 6
1610053.84209634459040.8272949161610124.02108984459093.087689087
1610184.17451283459137.8822189271610264.37251517459197.617335677
1610323.25592759459244.117898837  1610391.533022459298.932093665
#Sta/Elev= 30
       0 1056.46    18.4 1048.68    26.6 1043.87    38.9 1035.09    59.3 1024.92
    63.6 1021.36    67.5 1016.96    71.6  1014.2    82.3 1008.89    91.2 1002.19
   110.5  995.52   131.6   986.4   157.5  973.76   179.1  967.12     182  965.31
   192.5  954.35   194.9  952.73   206.6  952.06   224.4952.7333   239.5   955.7
   263.9  955.72   281.5  957.12     288  958.52   293.3  961.81   325.9  986.78
   343.4  997.78   372.8 1009.13   393.8 1021.18     409 1028.62   425.1  1032.3
#Mann= 3 ,-1,0
       0      .1       0   194.9    .045       0   224.4      .1       0
Bank Sta=194.9,224.4
XS Rating Curve= 0 ,0
Exp/Cntr(USF)=0,0
Exp/Cntr=0.3,0.1

Type RM Length L Ch R = 1 ,30914   ,341.5,340.3,331.6
XS GIS Cut Line= 5
1609922.10876401459308.2060252581610038.68368223459379.044771003
1610133.83343729459450.0864868461610215.86309776459475.965860337
1610298.68379825459506.099330261
#Sta/Elev= 30
       0 1037.34       9 1032.71    19.6 1029.28    33.2 1022.34    52.4 1006.22
    71.6  994.97    90.8  979.77   113.9  965.43     133  956.95   149.6  950.97
     159   949.8   194.1  949.88   198.8948.3538   208.2  947.61   227.8948.3708
   231.1   950.4   235.2  955.16   238.7  958.08   251.6  963.53   262.5   970.7
   279.7  987.44   289.1  997.59   296.9  1004.3   304.8 1014.31     310 1018.33
   317.5 1022.81   327.8 1027.66   369.6 1040.04   404.4 1058.18   429.3 1064.98
#Mann= 3 ,-1,0
       0      .1       0   198.8    .045       0   227.8      .1       0
Bank Sta=198.8,227.8
XS Rating Curve= 0 ,0
Exp/Cntr(USF)=0,0
Exp/Cntr=0.3,0.1

Type RM Length L Ch R = 1 ,30574   ,265.2,272.8,276.1
XS GIS Cut Line= 2
1609718.17017218459598.1178547881610108.17225478459748.316096453
#Sta/Elev= 30
       0   997.3       9  989.54    16.9  983.63    47.1  966.41    62.6  959.19
    76.7  957.38    87.3  954.19    97.8  955.11   118.9  952.15   171.6  948.31
   192.7  945.32   196.4943.7914   203.3  942.94   217.2  943.56   227.9  943.19
   231.7 943.825   238.4   948.5   252.7  953.22     273  956.94   287.6  963.62
   305.2  970.15   318.7  979.09   329.8   987.8   333.4  991.31   354.2 1018.01
   361.8 1024.19   371.9  1029.2   389.8 1034.85   396.6 1037.74   417.9 1050.49
#Mann= 3 ,-1,0
       0      .1       0   196.4    .045       0   231.7      .1       0
Bank Sta=196.4,231.7
XS Rating Curve= 0 ,0
Exp/Cntr(USF)=0,0
Exp/Cntr=0.3,0.1

Type RM Length L Ch R = 1 ,30301   ,311.7,300.7,292.2
XS GIS Cut Line= 6
1609634.82357742459775.4426235851609701.04457359459832.635094509
1609757.80627109459881.6566500071609833.48886251459947.018395916
1609890.25088809459996.039951429  1609957.490583460052.053290844
#Sta/Elev= 30
       0   988.8    18.4  972.55      27  966.22    31.3  963.61    43.6  958.09
    83.5   945.5    90.5  944.11    98.9  943.51   185.9  942.44   191.7  939.94
     196  939.17   206.8  939.12   220.9939.9417   226.4  941.15   235.1  941.84
   243.7  945.01   269.5   946.9   278.9  946.31   289.6  948.43   294.6  949.98
   308.7  957.79   318.5  962.47   337.1  976.63   356.1  992.39   370.6 1000.57
   377.5 1008.78   380.8 1012.16   396.2 1025.02   407.4 1030.06     425 1035.56
#Mann= 3 ,-1,0
       0      .1       0   191.7    .045       0   220.9      .1       0
#XS Ineff= 2 , 0
          162.13  948.84
Permanent Ineff=
       F       F
Bank Sta=191.7,220.9
XS Rating Curve= 0 ,0
Exp/Cntr(USF)=0,0
Exp/Cntr=0.3,0.1

Type RM Length L Ch R = 1 ,30001   ,303.4,304.1,302.3
XS GIS Cut Line= 6
1609453.08148684460162.5028730931609540.45401551460167.225960761
1609615.34461376460171.2745090871609715.12033284 460178.12521717
1609790.46106142460185.0773030071609826.63092422460186.803197054
#Sta/Elev= 30
       0 1033.36     8.6 1025.37    21.7 1016.23    32.2 1007.15      48   995.4
    61.2  982.36    67.7  976.75    82.1  968.13      94  963.23   113.7  957.33
   120.3  956.07   130.2  952.47     140  949.89   156.5  947.21   176.2  938.22
   189.3  937.86   195.8936.0333   199.2  935.08   227.6936.0109   251.8  936.62
   261.7  937.81   278.2  936.83   297.9  937.19   304.5  938.17   311.1  941.78
     321  949.56   337.5  958.09   360.5  974.93     367  977.74   374.4  979.07
#Mann= 3 ,-1,0
       0      .1       0   195.8    .045       0   227.6      .1       0
Bank Sta=195.8,227.6
XS Rating Curve= 0 ,0
Exp/Cntr(USF)=0,0
Exp/Cntr=0.3,0.1

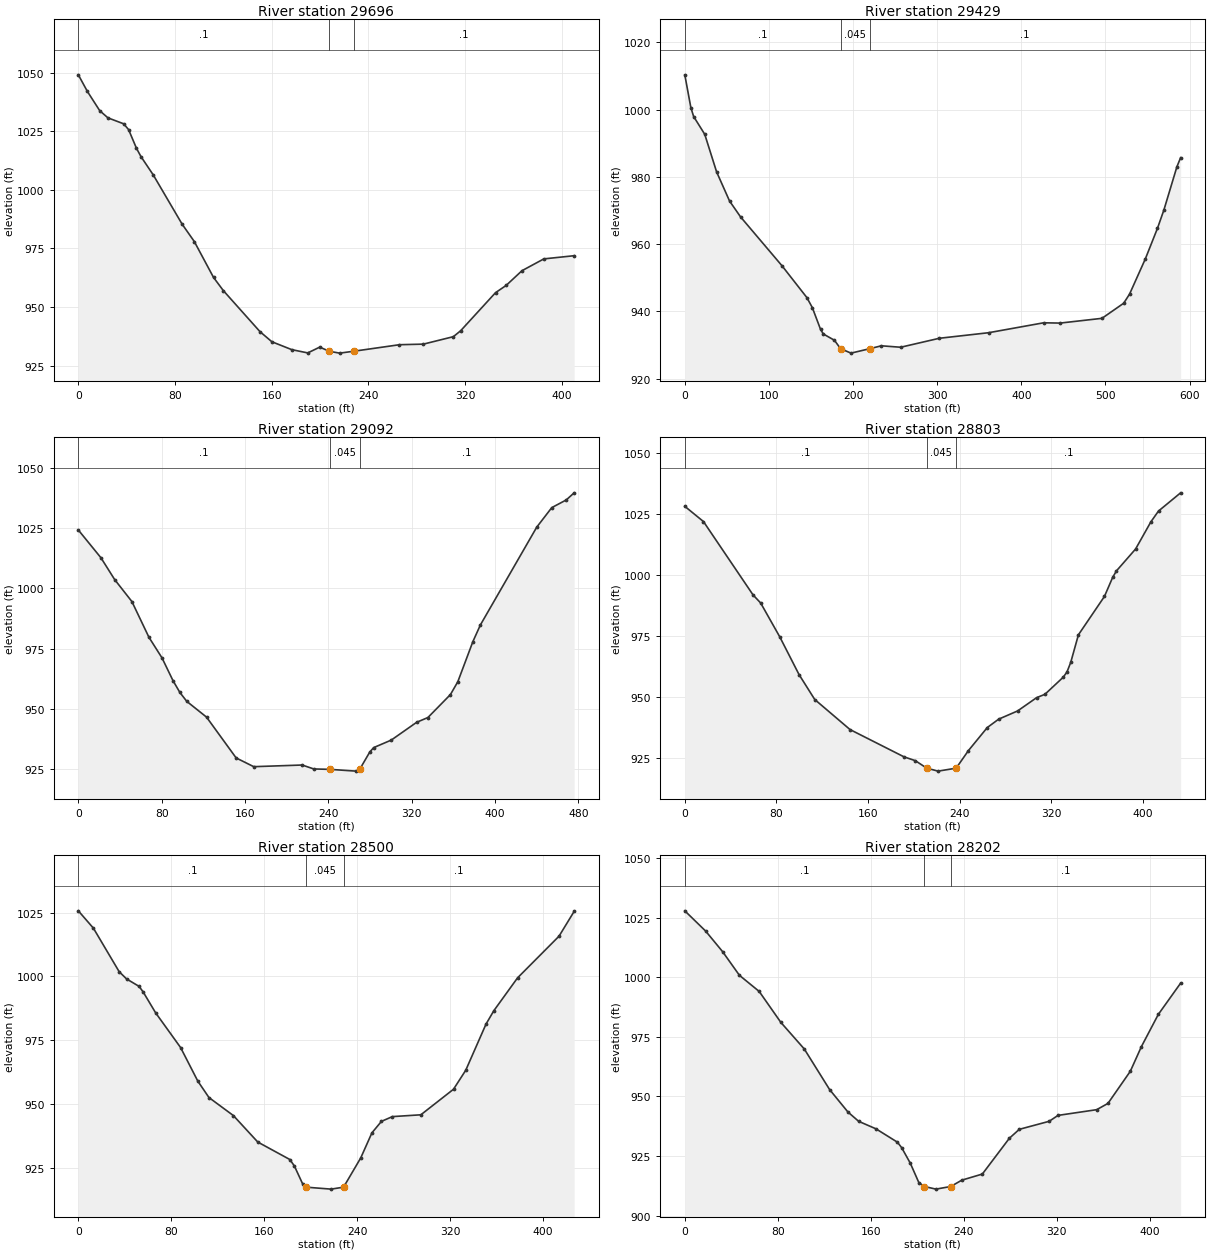
Type RM Length L Ch R = 1 ,29696   ,265.6,267.5,259.9
XS GIS Cut Line= 4
1609418.37189504460434.202257289 1609554.3471223460472.531126579
1609715.63817086460455.5317856151609795.95335922460384.954234829
#Sta/Elev= 30
       0 1049.08     7.5 1041.99    17.7 1033.79    24.5 1030.72    37.5 1028.19
    41.6 1025.71    48.1 1017.76    51.8 1014.23      62 1006.38    85.9  985.37
      96  977.94   111.9  962.64     120  957.02   150.4  939.47   160.2  935.18
   176.7  931.81   189.9  930.42   199.8  932.89   207.8 931.105   216.3  930.33
   227.8931.1246   265.8  933.92   285.6  934.17   310.4  937.35   316.4  939.85
   345.3  956.12   354.1  959.21   367.2   965.5   385.3  970.54   410.4   971.9
#Mann= 3 ,-1,0
       0      .1       0   207.8    .045       0   227.8      .1       0
Bank Sta=207.8,227.8
XS Rating Curve= 0 ,0
Exp/Cntr(USF)=0,0
Exp/Cntr=0.3,0.1

Type RM Length L Ch R = 1 ,29429   ,314.1,336.7,324
XS GIS Cut Line= 3
1609401.93516116460689.4270860911609749.03678191460683.222676019
1609943.59482942460538.824410999
#Sta/Elev= 30
       0 1010.38     7.2 1000.64    10.5  997.98    23.7  992.69    37.8  981.51
    53.2  972.84    66.3  968.11   115.5  953.59   145.1  944.12   151.6  941.13
   161.4  934.64   164.7  933.28   177.9  931.41   185.2928.9072   197.6  927.59
   219.9928.9136   233.7  929.77   256.6  929.34   302.6  932.01   361.1  933.66
   426.5  936.61   446.2  936.53   495.9  937.94   521.7  942.43   528.7  945.15
   547.5  955.65   561.9  964.74   569.5  970.16     585  983.04   589.4  985.74
#Mann= 3 ,-1,0
       0      .1       0   185.2    .045       0   219.9      .1       0
Bank Sta=185.2,219.9
XS Rating Curve= 0 ,0
Exp/Cntr(USF)=0,0
Exp/Cntr=0.3,0.1

Type RM Length L Ch R = 1 ,29092   ,287.3,289.6,284.3
XS GIS Cut Line= 5
1609420.41062042460856.4466951791609523.23685834460866.713078842
1609727.00187075460918.2201936691609795.27896518460949.256220832
1609874.93563001460985.464481756
#Sta/Elev= 30
       0 1024.31    21.7 1012.75    34.9 1003.67    51.4  994.55    67.8  979.66
    80.3  971.12    90.9  961.62    97.5  956.71   104.1  953.02   123.1  946.45
   151.5  929.48   168.4  925.84   214.9  926.53     226   924.9   241.6924.7211
   266.6  923.99   270.1924.7253   279.7  931.87   283.5  933.77   300.4   936.9
   324.8  944.31   335.6  946.29   357.2  955.83   364.3  961.17   378.8   977.9
     386  984.82   440.1  1025.5   454.5 1033.61   468.4 1036.81     476 1039.77
#Mann= 3 ,-1,0
       0      .1       0   241.6    .045       0   270.1      .1       0
Bank Sta=241.6,270.1
XS Rating Curve= 0 ,0
Exp/Cntr(USF)=0,0
Exp/Cntr=0.3,0.1

Type RM Length L Ch R = 1 ,28803   ,300.6,302.9,306.5
XS GIS Cut Line= 6
1609396.39459234461093.3405783331609488.85438117461109.208328754
1609561.83717485461130.8585479261609661.18736984461142.543235838
1609735.55992451461152.4431504161609821.82878084461168.029733419
#Sta/Elev= 30
       0 1028.27    16.3    1022    59.6  991.84    66.2  988.55    82.9  974.61
    99.7  959.13   113.4  948.89   144.2  936.54   191.3  925.33   201.2  923.75
   211.1920.6975     221  919.46   236.8 920.668   247.5  927.89     264  937.38
   273.9  940.81   290.4  944.18     307  949.64   314.3  951.03   330.2  958.03
   333.5  960.18   336.8  964.14   343.5  975.47   366.2  991.22   373.4  999.08
   376.7 1001.74   393.4 1010.73   406.7 1021.86   413.4 1026.33   432.7 1033.81
#Mann= 3 ,-1,0
       0      .1       0   211.1    .045       0   236.8      .1       0
Bank Sta=211.1,236.8
XS Rating Curve= 0 ,0
Exp/Cntr(USF)=0,0
Exp/Cntr=0.3,0.1

Type RM Length L Ch R = 1 ,28500   ,286.5,297.4,307.3
XS GIS Cut Line= 6
1609298.84229401461334.7580745071609380.27487393461369.791140929
1609451.13037525461395.6929920021609544.58884975461431.410440251
1609614.77834192461457.8290225861609696.64300759461488.641625002
#Sta/Elev= 30
       0 1025.66      13 1018.84    35.1 1001.83    41.5  998.97    52.3  996.04
    55.8  993.85    66.5  985.69      88  972.07   102.8  958.92   112.4  952.48
   133.4  945.42   154.4  935.04     182  928.19   185.9  925.64   192.9  918.74
   196.1917.3517   217.5  916.59   228.2917.3594     243  928.84   252.6  938.65
   260.8  943.15   270.2  945.01   294.7  945.72   322.8  955.74   333.3  963.16
   350.8   981.3   357.5  986.52   377.9  999.39   413.6 1015.73   426.6 1025.45
#Mann= 3 ,-1,0
       0      .1       0   196.1    .045       0   228.2      .1       0
Bank Sta=196.1,228.2
XS Rating Curve= 0 ,0
Exp/Cntr(USF)=0,0
Exp/Cntr=0.3,0.1

Type RM Length L Ch R = 1 ,28202   ,299.7,300.6,295.8
XS GIS Cut Line= 6
1609192.06396426 461407.567640171609233.29682143461484.707905844
1609268.64780059461550.8439284271609314.41936259461639.863763511
1609352.51672734461705.0053655061609396.31027493461782.024568424
#Sta/Elev= 30
       0 1027.92    17.9 1019.44    32.5  1010.8      47 1000.85      64  994.09
    82.6  981.12   102.8  969.93   124.6  952.89   140.4  943.45   149.6  939.56
   164.5  936.41   182.9  930.81   186.6   928.5     194     922   201.4  913.81
   206.2912.1976   216.1   911.1   228.8912.2003   238.3  914.86     256  917.43
   279.3  932.48   287.8   936.2   313.5  939.57   321.1  942.05   354.4  944.45
   364.1  947.09   383.3  960.56   392.9  970.96   407.4  984.44   426.6  997.56
#Mann= 3 ,-1,0
       0      .1       0   206.2    .045       0   228.8      .1       0
Bank Sta=206.2,228.8
XS Rating Curve= 0 ,0
Exp/Cntr(USF)=0,0
Exp/Cntr=0.3,0.1

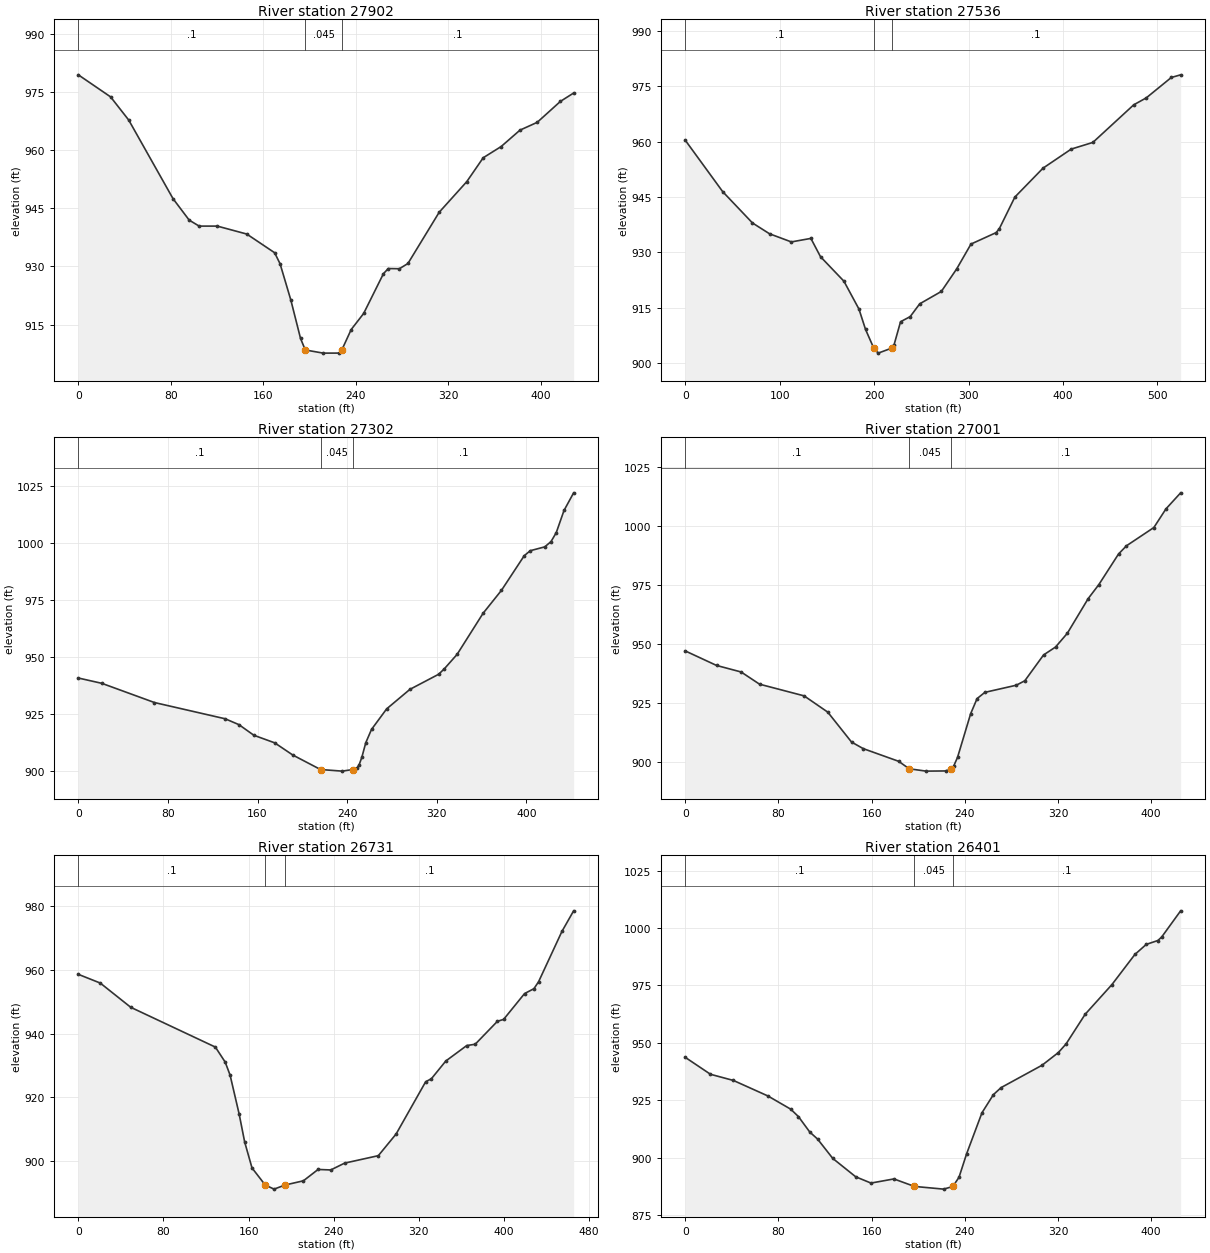
Type RM Length L Ch R = 1 ,27902   ,367.8,366,346
XS GIS Cut Line= 6
1608945.49785633461636.382471249 1609001.4235975461705.999129921
1609050.04882833461764.9248650821609112.96011984461842.869263008
1609160.45411934 461900.915078671609215.86345734461968.635087594
#Sta/Elev= 30
       0  979.41    27.9  973.73    43.6  967.75    81.9  947.49    95.9  941.95
   104.5  940.41   120.2  940.41   145.7  938.36   169.8  933.54   174.5   930.7
   183.8  921.36   192.2  911.45   196.3908.4778   211.8  907.66   225.8  907.67
   227.9908.4691     236  913.74   246.8  917.89   263.9  928.14   268.1  929.47
   277.7  929.42   285.1  930.77   312.1  943.97     336  951.88   350.2  958.03
   365.7  960.92     382  965.15   396.9  967.16     417  972.57   428.4  974.72
#Mann= 3 ,-1,0
       0      .1       0   196.3    .045       0   227.9      .1       0
Bank Sta=196.3,227.9
XS Rating Curve= 0 ,0
Exp/Cntr(USF)=0,0
Exp/Cntr=0.3,0.1

Type RM Length L Ch R = 1 ,27536   ,225.1,233.5,248.6
XS GIS Cut Line= 4
1608662.94212639461959.5296729281608786.15560548462000.909423921
1608958.75546373461955.6772361981609172.93465538461985.757761263
#Sta/Elev= 30
       0  960.32    39.6  946.44    71.1  937.98    89.2  935.05   112.3  932.85
     133   933.8   143.2  928.85     168  922.23   183.9  914.71   190.9  909.19
   199.6904.1334   204.3  902.78   218.5  904.12   221.2  905.11     228  911.27
   238.2  912.65   248.3  916.11   271.2  919.46   287.5  925.57   302.6  932.27
   329.2  935.36   332.6  936.42   349.1  944.98   378.9  952.79   408.8  957.95
   431.7  959.75     475  969.92   488.3   971.8   514.8  977.31   524.7  978.03
#Mann= 3 ,-1,0
       0      .1       0   199.6    .045       0   218.5      .1       0
Bank Sta=199.6,218.5
XS Rating Curve= 0 ,0
Exp/Cntr(USF)=0,0
Exp/Cntr=0.3,0.1

Type RM Length L Ch R = 1 ,27302   ,289,300.9,310.2
XS GIS Cut Line= 6
 1608640.5778625462094.9517640921608735.38115059462115.051133335
1608804.27208893462148.8174699991608880.96452084462214.588007763
1608940.15764393462264.6321990041609009.02627259462322.452621415
#Sta/Elev= 30
       0  940.77      21  938.43      68  929.98   131.1  922.84   143.4  920.25
   156.7  915.59   175.3  912.26   191.4  906.91   216.2900.5255   235.5  899.82
   245.3900.5283   248.7  901.19   250.6  902.55   253.1  905.96   256.6  912.34
   261.7  918.16   275.2  927.19     296  935.79   321.6  942.41   326.7  944.82
   338.1  951.17   361.3  969.25   377.7  979.34     398  994.55   403.4  996.76
   416.3  998.44   421.9 1000.75   426.6 1004.71   433.5 1014.44   442.1 1022.21
#Mann= 3 ,-1,0
       0      .1       0   216.2    .045       0   245.3      .1       0
Bank Sta=216.2,245.3
XS Rating Curve= 0 ,0
Exp/Cntr(USF)=0,0
Exp/Cntr=0.3,0.1

Type RM Length L Ch R = 1 ,27001   ,268.5,270,271.4
XS GIS Cut Line= 6
1608567.96350643462160.2213185881608593.46345542462244.131911919
1608612.09235518462316.8082757591608634.37413476462414.294301257
1608651.51353617462487.3108875011608673.81926584462571.968854666
#Sta/Elev= 30
       0  947.03    26.8  940.89    47.9  938.12    63.7  932.95     102  927.99
   122.3   921.1   142.7  908.42   152.8  905.62   183.2  900.25   192.2897.0845
   206.7  896.09   223.6  896.17   228.3897.0759   230.3  898.11   233.7  901.88
     245  920.44   250.5  926.83   257.2  929.48   284.2  932.51   291.5   934.4
   307.6  945.34   317.9   948.7     328  954.52   345.9  969.22   355.1  975.19
     372  988.15   378.8  991.62   402.3  999.35   412.7 1007.26   425.3 1014.06
#Mann= 3 ,-1,0
       0      .1       0   192.2    .045       0   228.3      .1       0
Bank Sta=192.2,228.3
XS Rating Curve= 0 ,0
Exp/Cntr(USF)=0,0
Exp/Cntr=0.3,0.1

Type RM Length L Ch R = 1 ,26731   ,345.7,330,324.2
XS GIS Cut Line= 4
1608305.12608992462210.8222463571608380.46880268 462445.86871317
1608449.11203809462517.9669941661608538.08561343 462596.95404093
#Sta/Elev= 30
       0  958.59    20.6  955.86    49.3  948.25   128.8  935.78     138  931.08
   142.6  927.01   151.1  914.83   156.3  906.05   163.2   897.9   175.6892.5518
   183.9  891.25   194.4892.5467   211.5  893.86   225.3  897.42   237.2  897.26
   250.2   899.4   281.9  901.74   298.6  908.53   326.4  924.93   331.7  925.84
   345.3  931.42     365  936.27   372.9  936.67   393.8  943.87   399.6  944.46
   419.3  952.56   428.1  954.09   432.5  956.29   454.4  972.04   465.4   978.5
#Mann= 3 ,-1,0
       0      .1       0   175.6    .045       0   194.4      .1       0
Bank Sta=175.6,194.4
XS Rating Curve= 0 ,0
Exp/Cntr(USF)=0,0
Exp/Cntr=0.3,0.1

Type RM Length L Ch R = 1 ,26401   ,303.7,311.1,315.7
XS GIS Cut Line= 6
1608114.58449192   462695.0722831608202.33530067462694.929566756
1608277.35024251462696.0525960031608377.27031825 462700.04996334
1608452.21045709462703.0476607531608539.64072843462706.545357168
#Sta/Elev= 30
       0  943.68    21.6  936.33    41.3  933.64    70.9  926.89    90.5  921.13
    97.1  917.92   106.9  911.15   113.5  908.15   126.6  899.69   146.3  891.68
   159.4  888.95   179.1  890.75   196.7887.4872   221.8  886.31   229.7887.4612
     235  891.48   241.5  901.67   254.7  919.56   264.5  927.45   271.1  930.52
   306.3  940.27   320.3  945.79   326.9  949.54   343.3  962.46   366.3   975.4
     386  988.51   395.8  992.91   405.7  994.58     409  996.11   425.3 1007.52
#Mann= 3 ,-1,0
       0      .1       0   196.7    .045       0   229.7      .1       0
Bank Sta=196.7,229.7
XS Rating Curve= 0 ,0
Exp/Cntr(USF)=0,0
Exp/Cntr=0.3,0.1