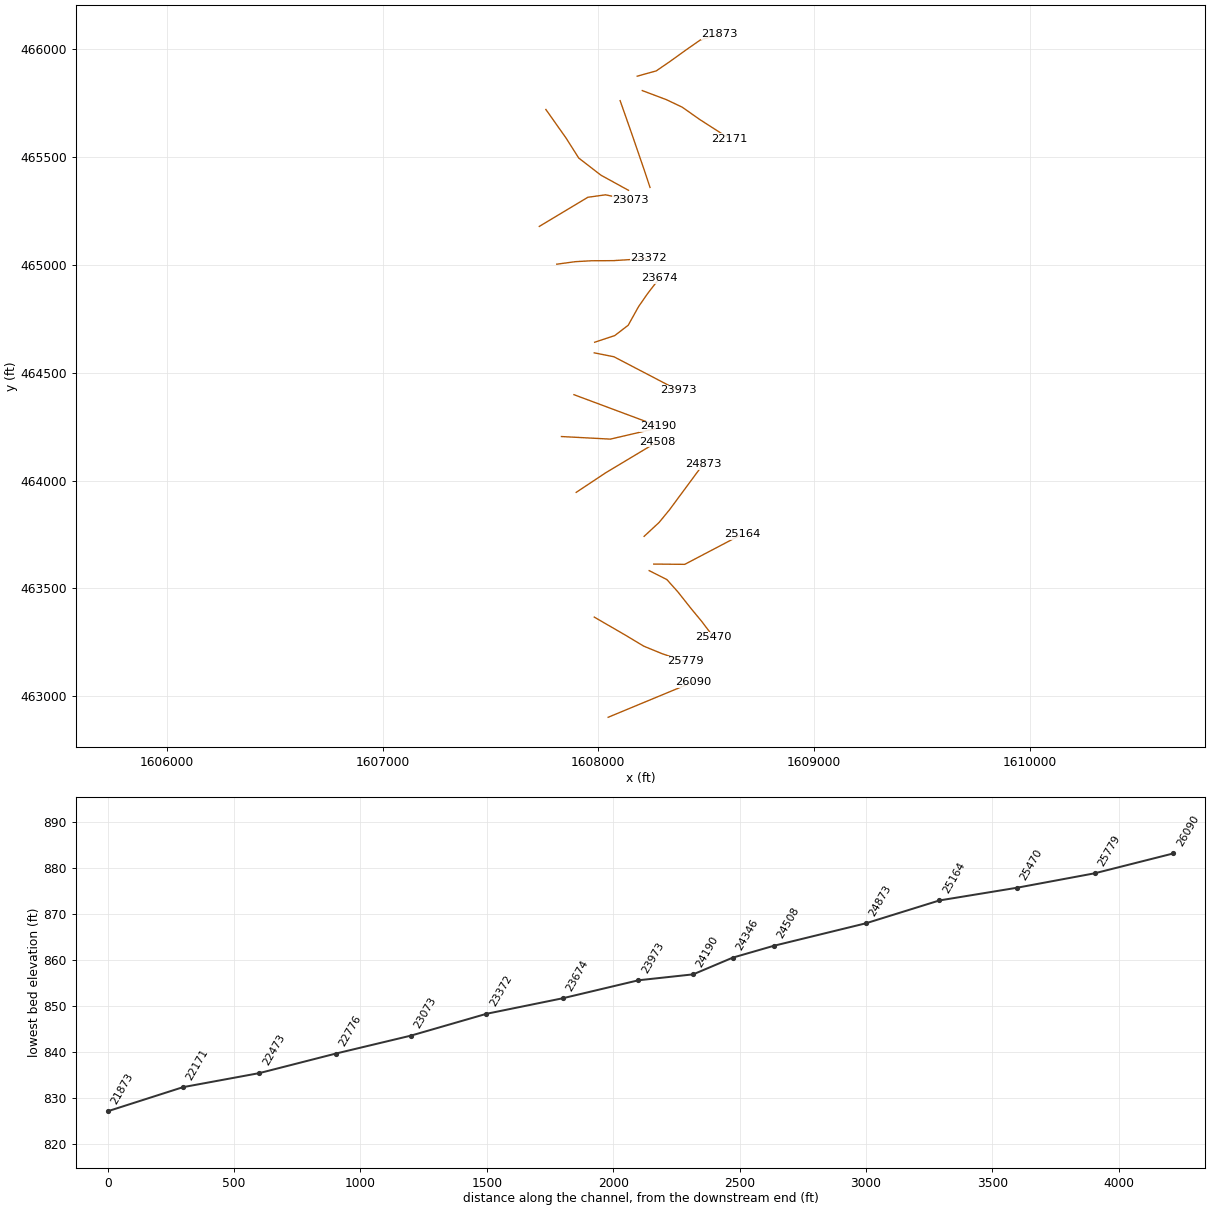
HEC-RAS study LngRn.prj: LngRn

--- LngRn.g01 (geometry) --- (continued)

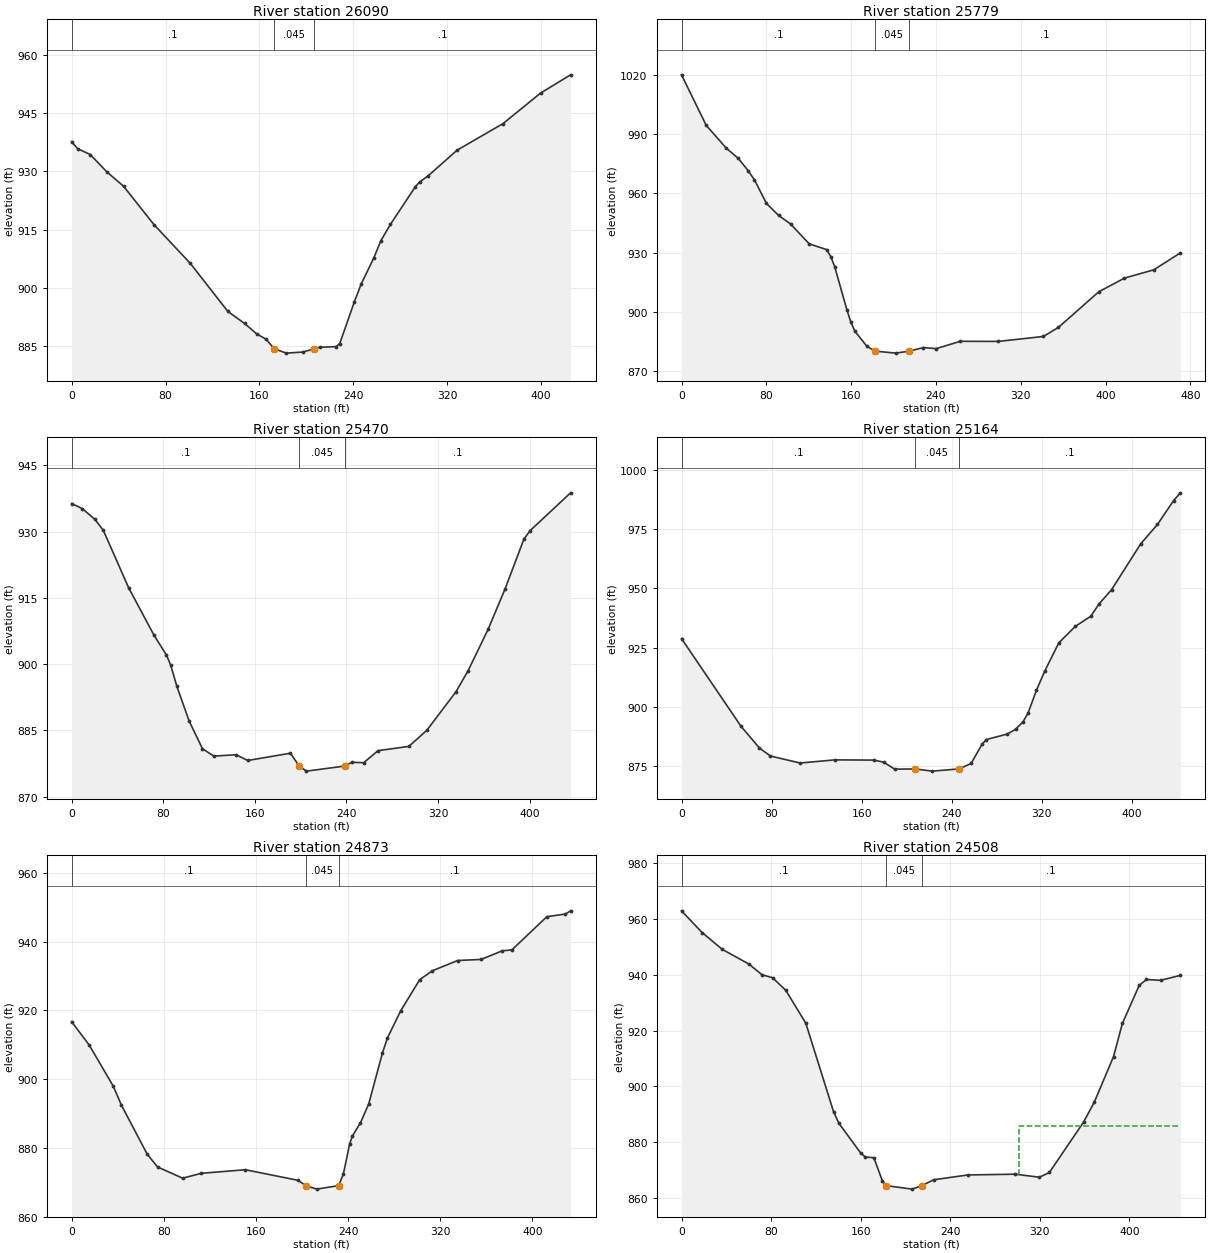
Type RM Length L Ch R = 1 ,26090   ,327.6,311,298.1
XS GIS Cut Line= 6
1608046.12695168 462902.667012171608126.95454593462936.180724666
1608196.23491918462964.9070451711608288.60940634 463003.20847775
 1608357.8897796463031.9344701771608438.71737383463065.448510751
#Sta/Elev= 30
       0  937.66     5.2  935.84    15.9  934.35      30  929.89    44.3  926.17
    70.2  916.29   101.1  906.34   133.1  893.96   147.3  890.87   157.9  888.12
   165.6  886.83   172.6884.3573   182.8  883.23     197  883.51   206.5  884.35
   211.2  884.73   225.4   884.9   228.4   885.7   240.9  896.49   246.7  901.06
   257.4  907.74   263.5  912.22   271.6  916.39   292.9  926.12   296.4  927.27
   303.7  928.87   328.4  935.48   367.5  942.32   399.4  950.16     425  954.87
#Mann= 3 ,-1,0
       0      .1       0   172.6    .045       0   206.5      .1       0
Bank Sta=172.6,206.5
XS Rating Curve= 0 ,0
Exp/Cntr(USF)=0,0
Exp/Cntr=0.3,0.1

Type RM Length L Ch R = 1 ,25779   ,314.3,308.9,303.9
XS GIS Cut Line= 6
1607981.57721201463367.0332094281608057.30212617463323.192089751
1608122.20882051   463285.6144091608211.01868226463232.300539255
1608296.99620059463197.0706228321608402.70760334463161.432242677
#Sta/Elev= 30
       0 1020.26    23.3   994.6    42.2  983.03    53.6  977.79    62.8  971.62
    68.8   966.9    80.1  954.97    91.5  948.88   102.9  944.49   120.5  934.38
     137  931.48   140.8  927.92   144.5  922.77     156  900.87   159.7  894.69
   163.5  890.05     175  882.28   182.9 879.905   202.1  878.91   214.5 879.886
   228.2  881.75   240.2  881.19     263  884.92   298.7  884.86   341.3  887.37
   355.4  891.94   393.6  910.09   417.8  917.02   445.5  921.24   470.6  929.86
#Mann= 3 ,-1,0
       0      .1       0   182.9    .045       0   214.5      .1       0
Bank Sta=182.9,214.5
XS Rating Curve= 0 ,0
Exp/Cntr(USF)=0,0
Exp/Cntr=0.3,0.1

Type RM Length L Ch R = 1 ,25470   ,277.7,306.5,327.9
XS GIS Cut Line= 6
1608236.15084983 463582.486846761608318.22417651463541.057795763
1608368.49802609463484.8541680131608430.70721926463406.362527087
 1608480.2159785463346.4285918331608534.91665651463274.317187503
#Sta/Elev= 30
       0  936.34     9.3  935.22    20.4  932.75    27.7  930.28    49.8  917.28
    71.8   906.6    82.8  902.05    86.5  899.78    91.9  894.96   102.6  887.12
   114.2  880.85   124.1  879.15   143.7  879.46   153.8  878.16   191.1  879.81
   198.7 876.894   205.1  875.75   238.7876.9056   244.8  877.76     255  877.65
   267.6  880.39   294.5  881.35   310.2     885   335.7  893.75   346.1  898.43
   363.8  907.92   378.6  917.08   394.9  928.26   400.3   930.2   435.7  938.78
#Mann= 3 ,-1,0
       0      .1       0   198.7    .045       0   238.7      .1       0
Bank Sta=198.7,238.7
XS Rating Curve= 0 ,0
Exp/Cntr(USF)=0,0
Exp/Cntr=0.3,0.1

Type RM Length L Ch R = 1 ,25164   ,281.1,290.7,294
XS GIS Cut Line= 3
1608257.32764475463612.8365235921608401.19971998463611.586182447
1608666.11819248463750.698960399
#Sta/Elev= 30
       0  928.82    52.8  891.91    69.2  882.72      79  879.35   105.3  876.41
   136.1  877.73   170.7  877.64   179.5  876.77   189.2  873.84   207.7   873.9
   222.6  872.99   246.6 873.915   257.2  876.23     267  884.39   270.7  886.29
   289.3  888.61   296.7  890.63   303.4  893.88   307.8   897.5   315.2  907.08
   322.8  915.36     335  926.99   349.6  933.93   363.4  938.22   370.8  943.44
   381.9  949.42   407.8  968.74   422.7  976.92     437  986.98   443.1  990.23
#Mann= 3 ,-1,0
       0      .1       0   207.7    .045       0   246.6      .1       0
Bank Sta=207.7,246.6
XS Rating Curve= 0 ,0
Exp/Cntr(USF)=0,0
Exp/Cntr=0.3,0.1

Type RM Length L Ch R = 1 ,24873   ,368.2,365.4,357.1
XS GIS Cut Line= 6
1608212.72045051463741.4192716781608282.35088867463806.016583428
1608330.37507084463864.5289335851608389.81458451 463944.94642368
1608434.39356358464005.2596232591608486.40231784464075.625296175
#Sta/Elev= 30
       0  916.72    15.2  909.96    36.1     898    43.3  892.41    65.7  878.14
    74.7  874.45    96.4   871.2   112.6  872.62   150.8  873.66   196.5  870.59
   203.4869.0281   212.8  868.02   231.8869.0375   235.9  872.35   241.4  881.16
   243.7  883.39   250.8  887.34     258  892.85   269.9  907.66   274.2  911.99
   285.6   919.8   302.2  928.94   313.2  931.53   335.2  934.51   355.6  934.83
   373.9  937.33   382.2  937.59   412.6  947.25   428.8  948.03   433.2  948.96
#Mann= 3 ,-1,0
       0      .1       0   203.4    .045       0   231.8      .1       0
Bank Sta=203.4,231.8
XS Rating Curve= 0 ,0
Exp/Cntr(USF)=0,0
Exp/Cntr=0.3,0.1

Type RM Length L Ch R = 1 ,24508   ,168.1,161.8,156.4
XS GIS Cut Line= 3
1607897.81747894463945.2639131161608035.46637365464036.636541391
1608276.06523501464180.771074958
#Sta/Elev= 30
       0  963.01    18.4  955.21    36.4  949.18    60.1  943.92    71.9  940.07
    81.4  938.97    93.2  934.44     111  922.69   135.8  890.92   140.5  886.81
   160.1  876.03   164.2  874.63   171.8  874.39   179.4   866.1   182.6864.3685
   206.2  863.11   214.7864.3723   225.3  866.48   255.9   868.2   298.1  868.47
   319.7  867.38   328.6  869.08   359.2  887.21   368.7  894.31   385.9  910.67
   393.8  922.59   408.9  936.28   415.3  938.36     428  938.07   445.7  939.86
#Mann= 3 ,-1,0
       0      .1       0   182.6    .045       0   214.7      .1       0
#XS Ineff= 2 , 0
                          301.87          885.89
Permanent Ineff=
       F       F
Bank Sta=182.6,214.7
XS Rating Curve= 0 ,0
Exp/Cntr(USF)=0,0
Exp/Cntr=0.3,0.1

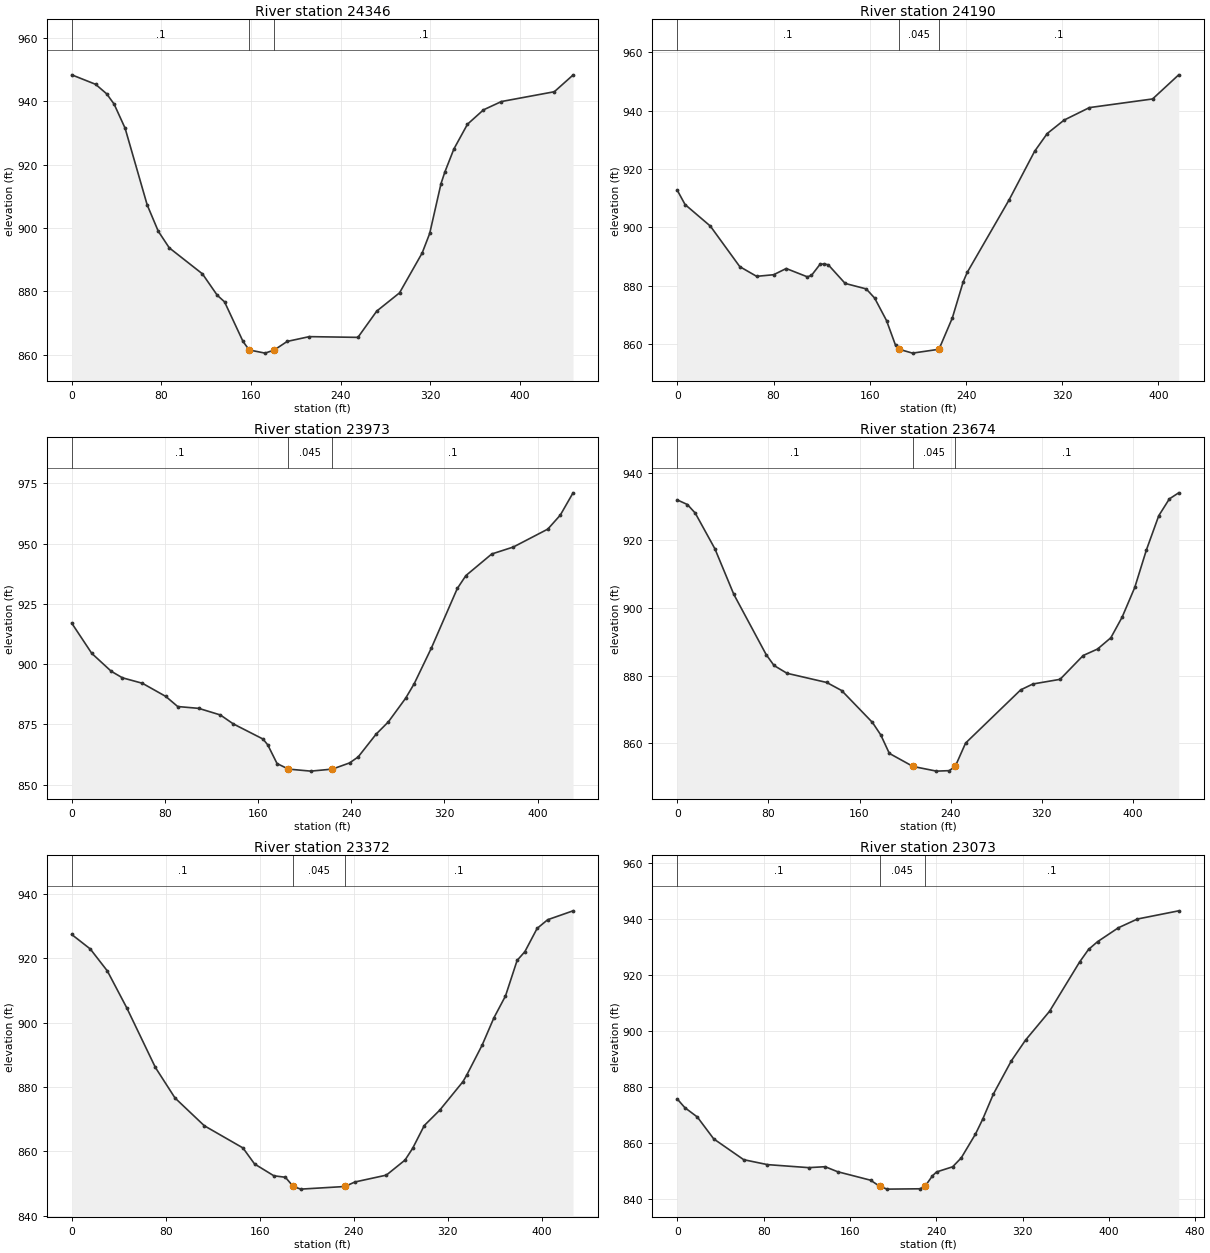
Type RM Length L Ch R = 1 ,24346   ,158,156.2,154
XS GIS Cut Line= 3
1607829.48604728464204.1319226761608056.33923875464192.156908421
1608270.58854169464242.178816032
#Sta/Elev= 30
       0  948.29    21.3   945.3    31.2  942.29    37.8  939.06    47.6  931.46
    67.3  907.28    77.2  898.97      87  893.74   116.6  885.53   129.8  878.79
   136.3  876.72   152.8  864.22   158.3861.5391   172.5  860.54   180.7861.5339
   192.2  864.23   211.9  865.74   255.3  865.51   272.1   873.8   292.4  879.54
   312.6  892.11   319.3  898.26   329.4  913.97   332.8  917.61   340.9  924.91
     353  932.71   367.3  937.25   383.3  939.87   430.5  942.96   447.2  948.23
#Mann= 3 ,-1,0
       0      .1       0   158.3    .045       0   180.7      .1       0
Bank Sta=158.3,180.7
XS Rating Curve= 0 ,0
Exp/Cntr(USF)=0,0
Exp/Cntr=0.3,0.1

Type RM Length L Ch R = 1 ,24190   ,219.3,216.6,215.3
XS GIS Cut Line= 2
1607887.43067855464398.1903728771608277.99149059464252.575403412
#Sta/Elev= 30
       0  912.68     6.4  907.84    27.4  900.46    51.9  886.55    65.9  883.23
      80  883.78    90.5  885.91     108  883.07   111.5  883.55   118.5   887.3
     122   887.5   125.5  887.17   139.5   880.8     157  878.92     164  875.79
   173.9  868.07   181.4  859.58   184.2  858.25   195.5  856.91   217.5858.2315
   228.6  868.96   237.6  881.31     241  884.59   275.9  909.51     297  926.08
   307.5  932.18   321.5  936.78   342.6  941.07   395.1  944.03   416.8   952.3
#Mann= 3 ,-1,0
       0      .1       0   184.2    .045       0   217.5      .1       0
Bank Sta=184.2,217.5
XS Rating Curve= 0 ,0
Exp/Cntr(USF)=0,0
Exp/Cntr=0.3,0.1

Type RM Length L Ch R = 1 ,23973   ,260,299.3,319.3
XS GIS Cut Line= 6
1607981.55457425464592.1626489161608072.75878817464574.015703589
1608139.25274967464539.3235157581608227.91103692464493.066062346
1608294.40467034464458.3735464221608371.98063068464417.898233667
#Sta/Elev= 30
       0     917    17.2  904.46    33.9  897.04    43.5  894.33    60.7  892.05
    80.8  886.59      91  882.41   109.1  881.65   127.6  878.92   138.7  875.22
   164.2  868.94   168.3  866.54   176.3  858.77   186.1  856.46   205.3  855.62
   223.8  856.46   238.6  859.02     246  861.52   261.4  870.97   271.9  876.05
   286.7  885.83   294.1  891.88   308.9  906.74   331.1  931.37   338.5  936.73
   360.7  945.68   379.2  948.56   408.8  955.99   419.5  961.77   430.5  971.04
#Mann= 3 ,-1,0
       0      .1       0   186.1    .045       0   223.8      .1       0
Bank Sta=186.1,223.8
XS Rating Curve= 0 ,0
Exp/Cntr(USF)=0,0
Exp/Cntr=0.3,0.1

Type RM Length L Ch R = 1 ,23674   ,324.7,302.3,282.2
XS GIS Cut Line= 6
1607983.51880917464641.2875506731608076.68758608464672.265835166
1608138.83149068464719.9550442551608187.50987101464807.319042757
1608230.65348551464869.2697062491608284.77181558464939.158346012
#Sta/Elev= 30
       0  931.94     8.8  930.59    15.7  928.06      33  917.47    49.6     904
      78  886.19    84.9  882.97    96.3  880.66   131.2  877.94   144.3  875.56
   171.4   866.1   178.7  862.41   186.2  856.96     207853.0937   227.6  851.71
   238.8  851.85   244.1853.0977   253.2  860.01   301.6  875.75   312.3  877.49
   336.2  878.87   356.5  885.92   369.1  887.83   380.8  891.17   390.7  897.26
   401.8  906.05   412.1  917.22   422.9  927.29   432.2  932.26   440.4  934.05
#Mann= 3 ,-1,0
       0      .1       0     207    .045       0   244.1      .1       0
Bank Sta=207,244.1
XS Rating Curve= 0 ,0
Exp/Cntr(USF)=0,0
Exp/Cntr=0.3,0.1

Type RM Length L Ch R = 1 ,23372   ,282.8,298.4,306.7
XS GIS Cut Line= 6
1607807.67500076465003.1765906661607894.79752992 465014.90753834
1607969.84888901465019.0830549151608069.89855768465019.579773083
1608145.05359109465024.3419026731608232.80899301465032.676531672
#Sta/Elev= 30
       0  927.32    15.8  922.82    30.3  916.01    46.8  904.58    71.2  886.06
    87.9  876.59   112.8  867.99   145.7   861.1   155.6  856.12     172  852.46
   181.8     852   188.5  849.14   194.9  848.32   232.5849.1354   240.9  850.53
   267.7  852.66   283.6  857.33   290.1  860.98     300  868.05   313.2  872.84
   332.9  881.66   336.2  883.75   349.3  893.05   359.2  901.43   369.1  908.24
     379  919.28   385.6  921.99     396   929.2     405   931.9   426.6  934.66
#Mann= 3 ,-1,0
       0      .1       0   188.5    .045       0   232.5      .1       0
Bank Sta=188.5,232.5
XS Rating Curve= 0 ,0
Exp/Cntr(USF)=0,0
Exp/Cntr=0.3,0.1

Type RM Length L Ch R = 1 ,23073   ,318.7,297.5,265.6
XS GIS Cut Line= 6
 1607726.7371705465178.2494032531607801.76753226 465223.26768592
1607866.07973959465261.8548790961607951.82891193465313.304579332
1608033.64469318465324.7989789251608150.77667676465300.166810334
#Sta/Elev= 30
       0  875.75     6.9  872.71    18.5  869.36    33.7  861.54    61.5   854.1
    83.5  852.34   121.7  851.26     137  851.59   148.5  849.81   179.1  846.77
   187.6  844.59   194.4  843.58     225   843.7   229.6844.5908   236.5  848.34
   240.3  849.72   255.2  851.56   263.2  854.75   276.4  863.27   283.1  868.58
     293  877.57   309.6   889.4   322.8  896.84   345.1  907.16   372.9  924.73
   381.2  929.24   389.6  932.02   408.9  936.99   426.5  940.11   464.8  943.04
#Mann= 3 ,-1,0
       0      .1       0   187.6    .045       0   229.6      .1       0
Bank Sta=187.6,229.6
XS Rating Curve= 0 ,0
Exp/Cntr(USF)=0,0
Exp/Cntr=0.3,0.1

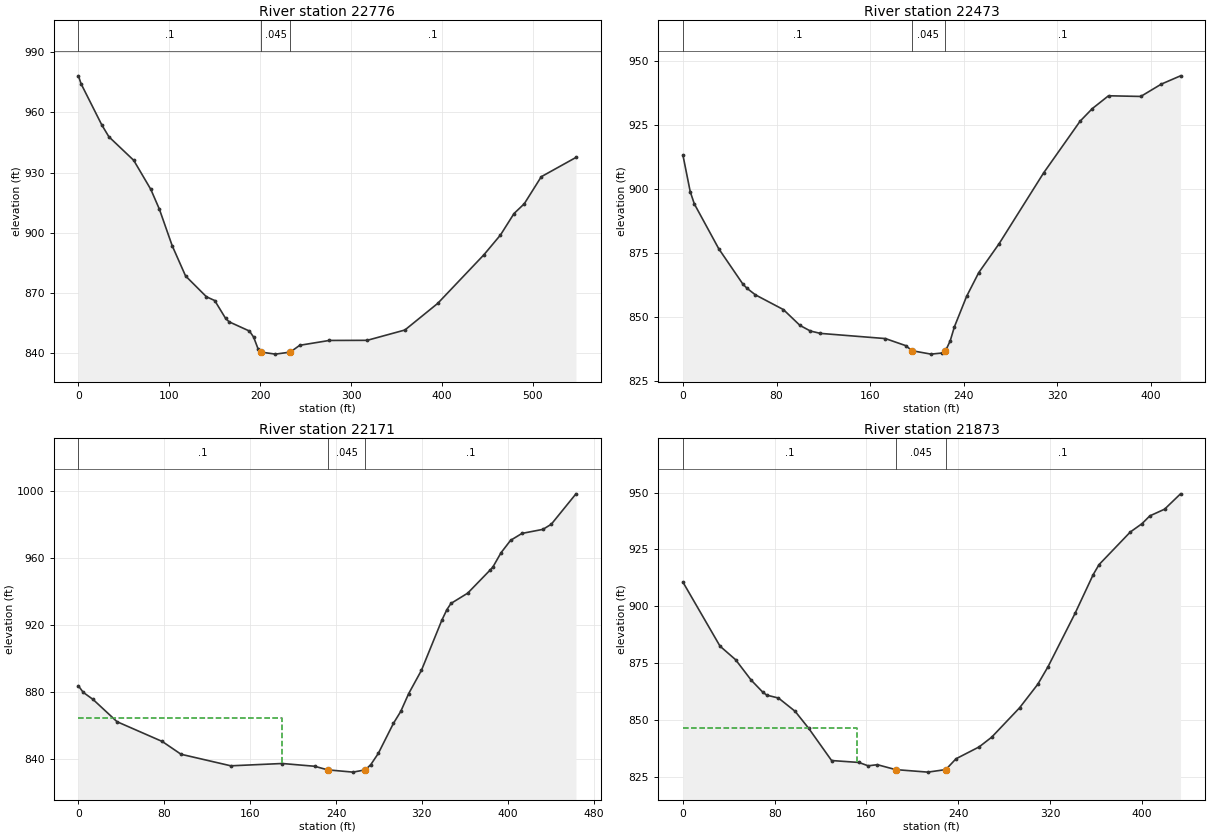
Type RM Length L Ch R = 1 ,22776   ,301.7,302.5,292.7
XS GIS Cut Line= 6
1607757.27188633465720.393988252 1607807.7314311465648.909223095
1607850.98232885465587.6363797491607909.57965259465495.280265257
 1608012.5200635465415.786985919   1608140.21469465345.660813838
#Sta/Elev= 30
       0  978.23     2.9  974.29    25.6  953.89    33.5  947.91    60.9  936.14
    79.7  921.67    89.1  911.84   103.2  893.65   117.9  878.61   140.9  868.22
     150  866.35     162  857.45   165.9  855.75   188.2  851.16   192.8  848.17
   197.7  842.31   201.3840.6625   216.8  839.67   233.1840.6714   243.6  844.07
   276.1  846.48   317.8  846.54   359.3  851.68   395.4  864.92   446.3  889.16
   464.5  898.99   479.4  909.67   490.7  914.54   509.4     928   547.6   937.6
#Mann= 3 ,-1,0
       0      .1       0   201.3    .045       0   233.1      .1       0
Bank Sta=201.3,233.1
XS Rating Curve= 0 ,0
Exp/Cntr(USF)=0,0
Exp/Cntr=0.3,0.1

Type RM Length L Ch R = 1 ,22473   ,289.8,302.2,310.8
XS GIS Cut Line= 6
1608101.53071226465761.2193659251608130.54476184465678.673271179
1608155.41413467465607.9178352511608187.93408276465513.353063762
1608212.31133059465442.412916929 1608240.1101595465358.973779336
#Sta/Elev= 30
       0  913.12     6.2  898.95     9.7  894.16    30.6  876.62    51.4  862.69
    54.9  861.11    61.9  858.61    85.9  852.83   100.1  846.63     109  844.45
   117.5  843.53   173.1   841.5   190.5  838.74   195.9836.7535   212.1  835.42
   221.7  835.86   223.7 836.715   225.2  837.35   228.6   840.7   232.1  846.08
   242.5  857.95   252.9  867.26   270.3  878.56   308.4  906.26   339.6  926.48
     350  931.39   363.9  936.42   391.5  936.16   409.1  940.99   425.5  944.22
#Mann= 3 ,-1,0
       0      .1       0   195.9    .045       0   223.7      .1       0
Bank Sta=195.9,223.7
XS Rating Curve= 0 ,0
Exp/Cntr(USF)=0,0
Exp/Cntr=0.3,0.1

Type RM Length L Ch R = 1 ,22171   ,269.1,297.8,315.8
XS GIS Cut Line= 6
1608204.22342026465807.988629341  1608316.379692465765.777099594
1608389.66399425465730.9011850951608471.51652084465673.291064084
1608534.65779875465632.8164075021608608.32234959465585.596029505
#Sta/Elev= 30
       0  883.86     4.5  879.98    13.6  875.78      36  862.46    78.1  850.67
    95.6  843.03     142  836.13   189.9  837.51   220.1  835.86   232.2833.7231
   255.9  832.36   267.3833.7238   272.4  836.83   279.4  843.52   293.5  861.48
   300.3  868.57   307.7  879.23   319.6  893.14   338.6  923.06   343.3  929.36
   347.1  933.08   362.7  939.23   383.7  953.09   386.1  954.76   393.8  963.41
   402.7  970.79   413.3  974.91   432.8  977.32   440.6  980.38   463.6  998.54
#Mann= 3 ,-1,0
       0      .1       0   232.2    .045       0   267.3      .1       0
#XS Ineff= 2 , 0
          189.53  864.73
Permanent Ineff=
       F       F
Bank Sta=232.2,267.3
XS Rating Curve= 0 ,0
Exp/Cntr(USF)=0,0
Exp/Cntr=0.3,0.1

Type RM Length L Ch R = 1 ,21873   ,324.6,300,287.1
XS GIS Cut Line= 6
1608180.59977984465874.7581808421608269.13208309465899.316202596
1608330.97152634465941.7810126691608412.22103576466000.077812091
1608473.75076833466042.9743798381608562.17021093466068.260746583
#Sta/Elev= 30
       0  910.62    32.3  882.51    45.9  876.54    59.5  867.56    69.7  862.22
    73.1  860.97    83.3  859.69    97.8  853.86   109.7  846.33   129.6  832.22
   153.5  831.37   161.5  829.89   169.5  830.39   185.4828.2333   213.5  827.12
   229.2828.2372   238.1  832.99   258.3  838.22   269.2  842.48   293.5  855.38
   309.4  865.74   318.4  873.51   341.9   896.9   357.7  913.92   362.8  918.33
   390.1  932.69   400.3  936.35   407.1  939.77     420  942.72   433.9  949.47
#Mann= 3 ,-1,0
       0      .1       0   185.4    .045       0   229.2      .1       0
#XS Ineff= 2 , 0
          151.62  846.62
Permanent Ineff=
       F       F
Bank Sta=185.4,229.2
XS Rating Curve= 0 ,0
Exp/Cntr(USF)=0,0
Exp/Cntr=0.3,0.1