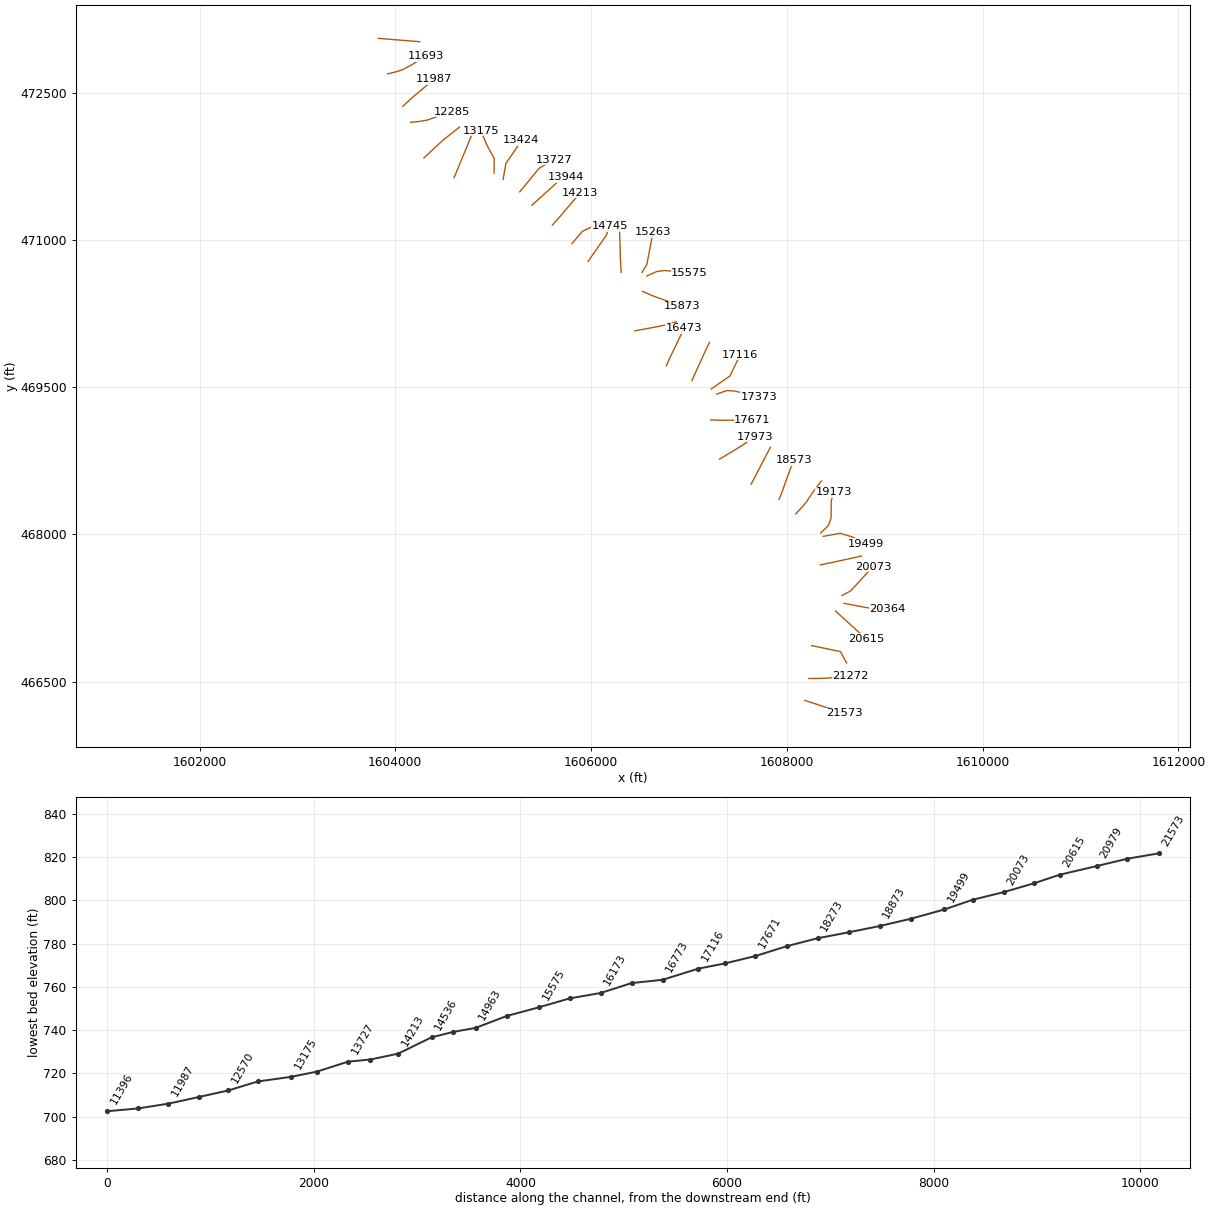
HEC-RAS study LngRn.prj: LngRn

--- LngRn.g01 (geometry) --- (continued)

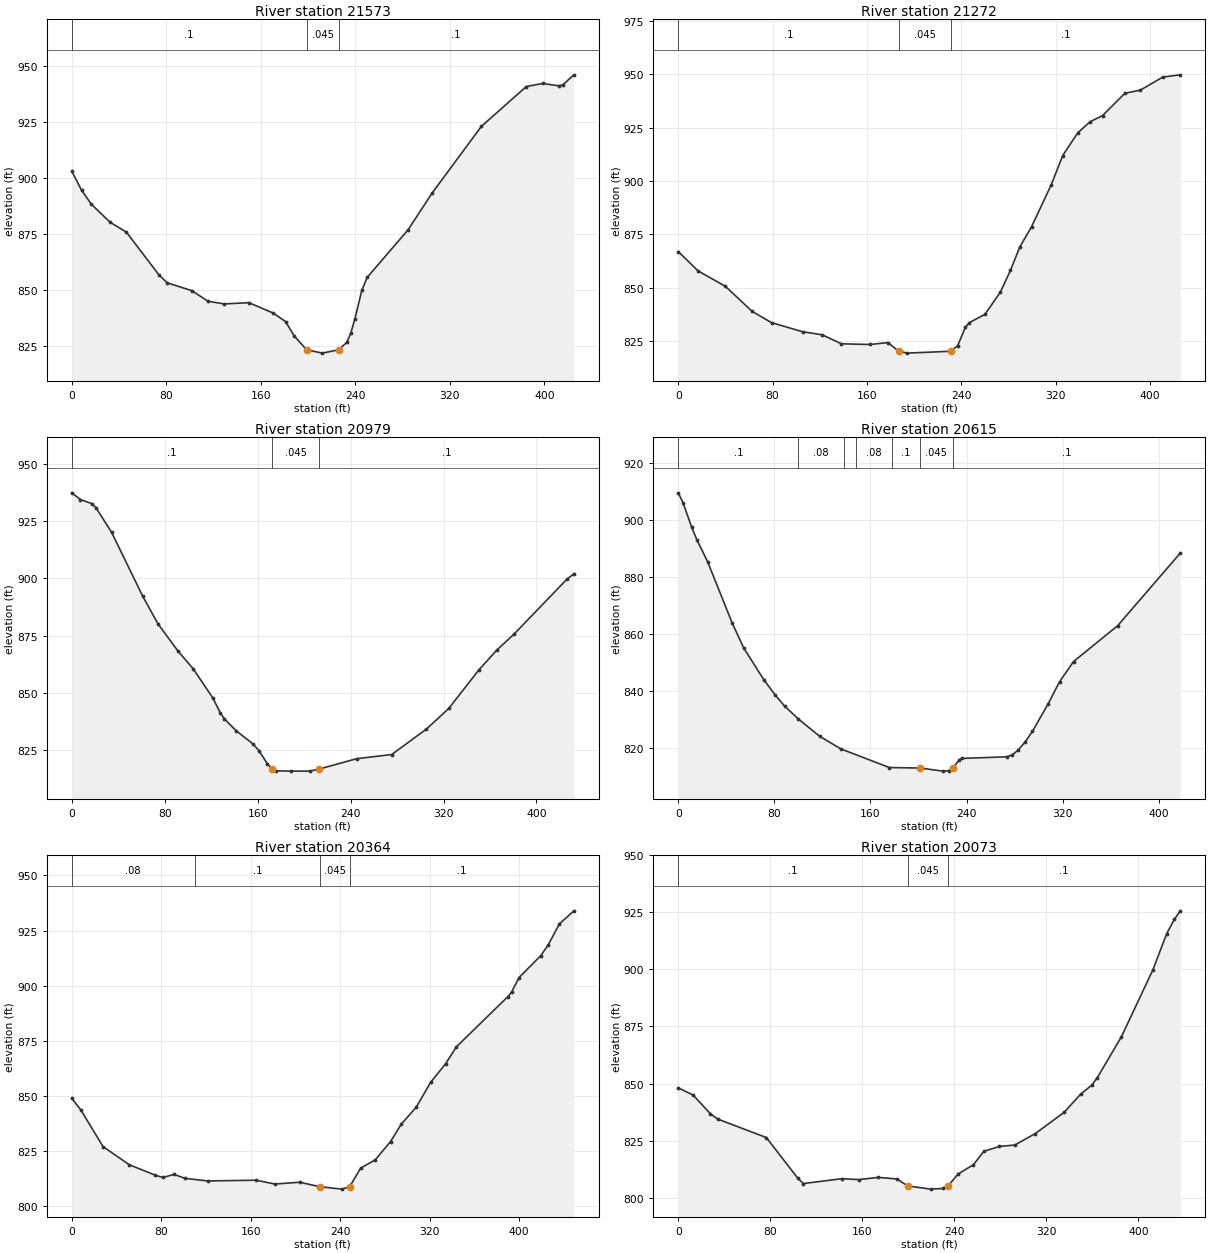
Type RM Length L Ch R = 1 ,21573   ,292.8,301.2,307.1
XS GIS Cut Line= 6
1608184.07713509466309.8593447511608267.21902917466282.588073835
1608338.48299426466259.212136343 1608433.5018331466228.044219673
1608504.76579817466204.667954087 1608587.9070361466177.396026999
#Sta/Elev= 30
       0  903.12     8.3  894.59    16.7  888.23    32.5  880.26    46.3  875.82
    73.9  856.62    80.8  853.16   101.6  849.65   115.4  844.88   129.2  843.71
   149.9  844.27   170.6   839.6     181  835.81   188.3  829.36   198.8823.1934
   212.1  821.69   225.9  823.18   232.8   826.5   236.2  830.63   239.7  837.08
   245.5  849.73     250  855.55   284.6  876.83   305.3  893.54   346.7  923.15
   384.7  940.97   398.5  942.37   412.3  941.31   415.8  941.82     425  946.24
#Mann= 3 ,-1,0
       0      .1       0   198.8    .045       0   225.9      .1       0
Bank Sta=198.8,225.9
XS Rating Curve= 0 ,0
Exp/Cntr(USF)=0,0
Exp/Cntr=0.3,0.1

Type RM Length L Ch R = 1 ,21272   ,298.6,292.6,287
XS GIS Cut Line= 6
1608224.32410184466532.9166414291608312.21401793466533.173858762
1608387.39103292   466535.0055481608487.14477043466542.392016172
1608561.79094659466549.6685764191608648.87837084466558.158060759
#Sta/Elev= 30
       0  866.87    16.9  857.77    39.9  850.62    62.6  838.83    79.2   833.5
   105.5  829.27   121.9  827.86   138.3  823.62   162.4  823.29   177.8  824.19
   186.9820.1122   194.2  819.24   230.8  820.12   236.9  822.74   243.5  831.47
   246.8  833.56     260  837.42   273.1  847.88   281.6  858.07   289.6  869.06
   299.5  878.53     316  897.94   325.9   911.9   338.6  922.52     349  927.72
   359.7  930.65   378.6   941.1   391.8   942.6   410.7   948.7   425.6  949.76
#Mann= 3 ,-1,0
       0      .1       0   186.9    .045       0   230.8      .1       0
Bank Sta=186.9,230.8
XS Rating Curve= 0 ,0
Exp/Cntr(USF)=0,0
Exp/Cntr=0.3,0.1

Type RM Length L Ch R = 1 ,20979   ,374.1,364.3,354.5
XS GIS Cut Line= 3
1608253.59348586466867.3344897651608547.42318838466807.002335863
1608611.19878328466691.106609876
#Sta/Elev= 30
       0   937.4     7.5  934.45    17.5  932.66    20.9  930.84    34.3  920.15
      61  892.32    74.4  880.05    91.2  868.48   104.6  860.52   121.3  847.94
     128  841.24   131.4   838.7   141.4  833.56   156.1  827.73   161.5   824.6
   168.2  819.22   172.1816.8364   175.5  816.04   188.3  815.89   205.1  815.91
   213.2816.8268   245.3  821.33   275.4  823.13   305.3  834.25   324.5  843.24
   350.7  860.24   365.7  868.65   380.7   875.7   426.1  899.63   432.2  902.04
#Mann= 3 ,-1,0
       0      .1       0   172.1    .045       0   213.2      .1       0
Bank Sta=172.1,213.2
XS Rating Curve= 0 ,0
Exp/Cntr(USF)=0,0
Exp/Cntr=0.3,0.1

Type RM Length L Ch R = 1 ,20615   ,243.7,251.3,257.4
XS GIS Cut Line= 3
1608498.74909631467219.2761278651608593.05679985467133.108546039
1608808.12929112466938.164714092
#Sta/Elev= 30
       0  909.45       4  906.02    11.1  897.47    15.6  892.93    24.5  885.25
    44.8   863.9    54.5  855.04    71.3  843.86    80.6  838.59    88.6  834.63
     100  830.11   117.8  824.03   135.5  819.59   175.8  813.08   201.4   812.9
   220.3  811.82   225.2  811.95   228.5   812.9   233.9  815.71   236.2  816.28
   273.4  816.84     278  817.51   282.7   819.1   288.7  821.96   294.9  825.78
   307.9  835.39   317.5  843.21   329.1  850.26   365.8  862.82     418  888.33
#Mann= 7 ,-1,0
       0      .1       0     100     .08       0  137.75      .1       0
  147.75     .08       0  177.75      .1       0   201.4    .045       0
   228.5      .1       0
Bank Sta=201.4,228.5
XS Rating Curve= 0 ,0
Exp/Cntr(USF)=0,0
Exp/Cntr=0.3,0.1

Type RM Length L Ch R = 1 ,20364   ,270.2,290.6,301.7
XS GIS Cut Line= 4
1608584.38768618467297.7576314211608866.06888135 467244.94605726
1608941.06873134 467244.946057261609028.56855634 467244.94605726
#Sta/Elev= 30
       0  848.93       8   843.8      28  827.07    51.4  818.87    74.8  814.12
    81.4  813.09    91.5  814.47   101.5  812.68   121.5  811.52   164.9  811.85
   181.6  810.12   203.9  810.93   221.9 808.909   241.7  807.81   248.6 808.925
   258.4  817.32   271.4  821.08   285.1  829.34   294.9  837.37   308.1  844.94
     321   856.2   334.3   864.6   344.1  872.34   390.1  895.06   393.4   897.1
     400  903.66   419.6  913.69   426.2  918.52   436.1  927.98   449.1  933.95
#Mann= 4 ,-1,0
       0     .08       0     110      .1       0   221.9    .045       0
   248.6      .1       0
Bank Sta=221.9,248.6
XS Rating Curve= 0 ,0
Exp/Cntr(USF)=0,0
Exp/Cntr=0.3,0.1

Type RM Length L Ch R = 1 ,20073   ,306.3,300,285
XS GIS Cut Line= 6
1608564.42250301467376.9891002631608651.19463918467424.531328008
1608702.22865784467479.4908637551608770.27379733467552.770244762
1608821.30781601 467607.729780511608880.84706701467671.849074841
#Sta/Elev= 30
       0  848.13      13  844.94      28  836.75    34.3  834.46    76.6  826.36
   103.9  808.58   108.8  806.22   142.5  808.36     157  807.94   173.8  808.92
   190.1  808.24   199.5 805.147   219.7  803.78   229.8  804.06   234.5805.1391
   243.2  810.38   256.6  814.49   265.6  820.31     279  822.46   292.5  823.08
   310.4  828.12   335.4  837.39   349.8  845.36   359.5  849.33   364.3  852.64
   385.1   870.4   412.5  899.73   424.6  915.68   431.2  921.88   436.4  925.64
#Mann= 3 ,-1,0
       0      .1       0   199.5    .045       0   234.5      .1       0
Bank Sta=199.5,234.5
XS Rating Curve= 0 ,0
Exp/Cntr(USF)=0,0
Exp/Cntr=0.3,0.1

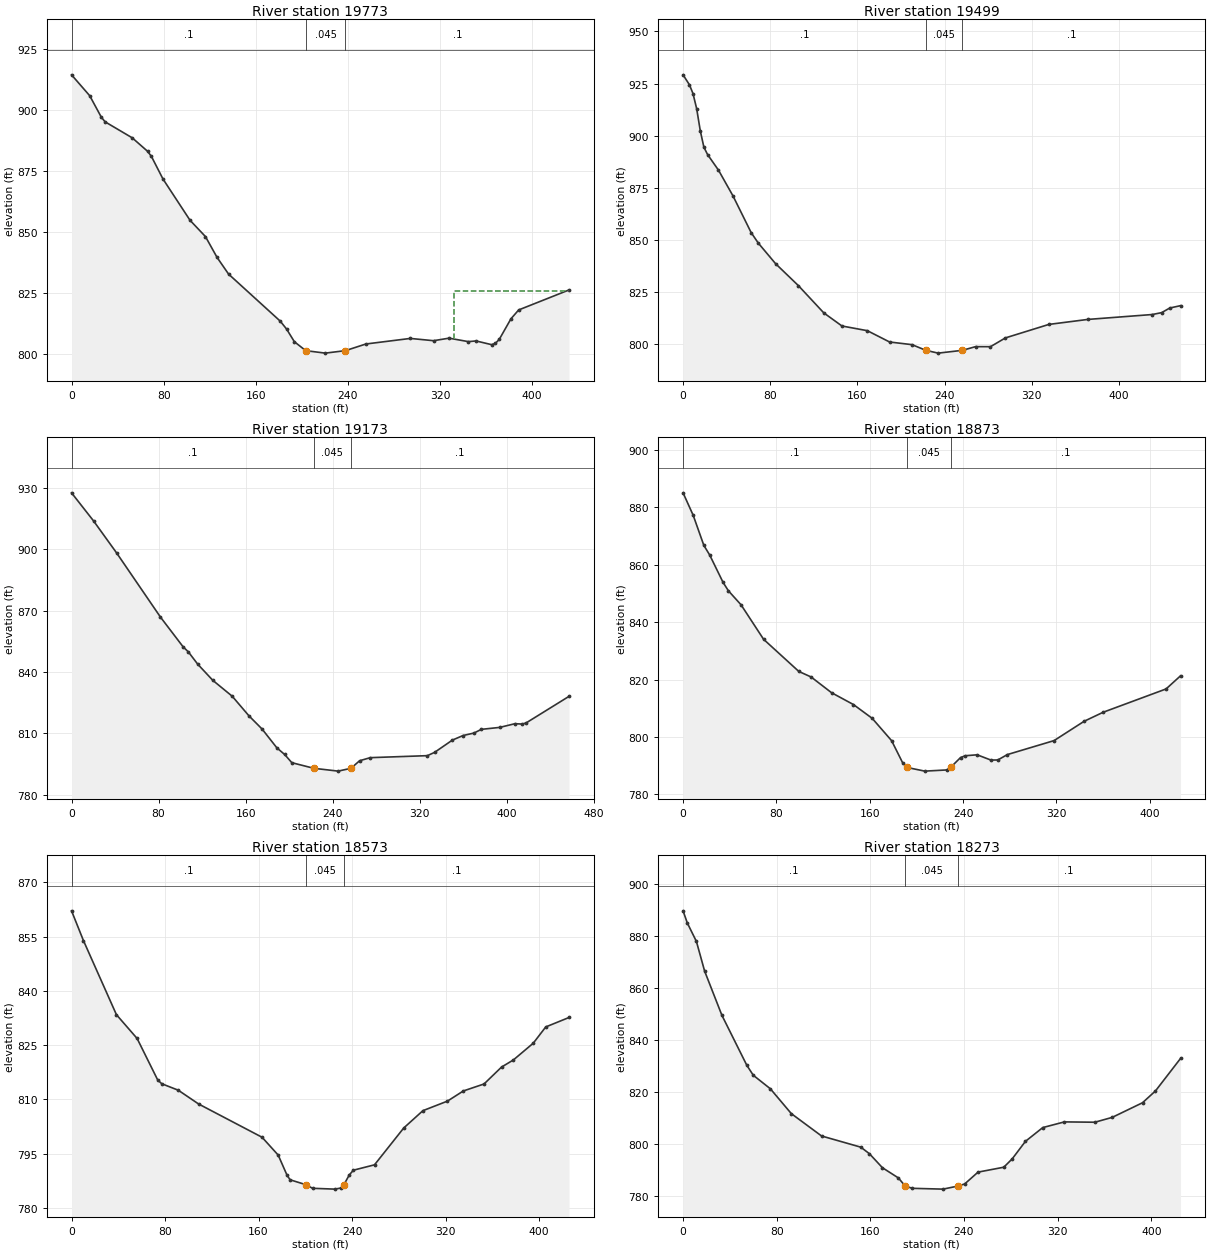
Type RM Length L Ch R = 1 ,19773   ,278.2,273.8,260.2
XS GIS Cut Line= 6
1608340.50858076 467689.163672761608426.30138817467706.415934846
1608499.65065092467722.0687906741608597.36830325467743.311202258
1608670.65654251467759.2445693461608762.80071518467780.244199261
#Sta/Elev= 30
       0  914.27    15.8   905.7    25.9  896.88    29.2     895    52.7  888.46
      66  882.96    69.4  880.82    79.4   871.6   102.9  854.68   116.3     848
   126.4  839.45   136.4  832.62   181.2  813.38   186.7  810.15   193.5  804.93
   203.4  801.27   220.4  800.26   237.9801.2839   255.6     804   294.2  806.28
   314.4  805.35   327.8  806.39   344.6  804.97   351.3  805.25   364.8  803.73
   368.1  804.26   371.5  805.95   381.6  814.34   388.3  817.96     432  826.14
#Mann= 3 ,-1,0
       0      .1       0   203.4    .045       0   237.9      .1       0
#XS Ineff= 2 , 0
                          331.83          825.74
Permanent Ineff=
       F       F
Bank Sta=203.4,237.9
XS Rating Curve= 0 ,0
Exp/Cntr(USF)=0,0
Exp/Cntr=0.3,0.1

Type RM Length L Ch R = 1 ,19499   ,292.5,326.8,355.6
XS GIS Cut Line= 4
1608373.31560175467980.2572506671608546.10722612468011.484845219
1608673.15852342467972.837337165 1608804.4389672467904.217162811
#Sta/Elev= 30
       0  929.21     5.8  924.47     9.1  920.24    12.5  912.91    15.8  902.36
    19.1  894.52    22.5  890.97    32.5   883.5    45.8  871.16    62.5  853.54
    69.1  848.48      85   838.6   105.8  828.15   129.1  815.08   145.8  808.78
   169.1  806.53   189.5  801.11   210.1  799.83   222.8797.1074   234.1  795.77
   256.4 797.115   268.4  798.88   282.1  798.86   295.8  803.07   335.7  809.54
   371.4  811.93   430.5  814.28   439.2  815.19   446.6   817.4   456.5  818.53
#Mann= 3 ,-1,0
       0      .1       0   222.8    .045       0   256.4      .1       0
Bank Sta=222.8,256.4
XS Rating Curve= 0 ,0
Exp/Cntr(USF)=0,0
Exp/Cntr=0.3,0.1

Type RM Length L Ch R = 1 ,19173   ,308.6,299.5,289.6
XS GIS Cut Line= 6
1608344.70870359468013.2621059271608425.94016843468091.608077839
1608452.67207034 468166.339883761608453.75080834468266.340011835
1608453.75080834 468341.339861841608479.68743625468427.627746999
#Sta/Elev= 30
       0  927.65    20.3  913.86    41.5  898.19    81.7  866.87   102.6  852.26
   107.3  849.87     116  843.79   129.9  835.87   147.7  828.11   163.1  818.51
   175.2  812.03   188.8  802.82   195.9  799.61   202.5  795.59   222.7792.8436
   245.1  791.46   256.9 792.848   264.8  796.54   274.6  798.05   327.1  799.03
   333.7  800.63   350.1  806.65   359.9  808.88   369.9  810.09   376.7   811.9
   393.6  812.86   407.6  814.67   414.4  814.49   417.9  815.06   457.3  828.05
#Mann= 3 ,-1,0
       0      .1       0   222.7    .045       0   256.9      .1       0
Bank Sta=222.7,256.9
XS Rating Curve= 0 ,0
Exp/Cntr(USF)=0,0
Exp/Cntr=0.3,0.1

Type RM Length L Ch R = 1 ,18873   ,297.2,299.8,304.3
XS GIS Cut Line= 6
1608090.88900125 468209.633104251608152.00666118468273.194985002
1608200.21489809468331.0987405931608255.59274009468414.364978254
1608299.80098501468475.0361167491608353.14700693 468544.64194867
#Sta/Elev= 30
       0  884.97     8.7  877.12    17.8  866.68    22.8  863.34    34.2  853.86
    38.8   850.9    49.7  845.99      69     834    99.2  822.81   109.7  820.89
   127.2  815.42     146  811.29   162.1  806.48   178.7  798.72   188.1  791.07
   191.9789.3982   207.1  788.12     226  788.53   229.2  789.39   237.8  792.85
   241.9  793.48     252   793.8   263.8  791.97   269.7     792   277.9  793.88
   317.9  798.74   343.7  805.47     360  808.61   413.9  816.72   426.3  821.29
#Mann= 3 ,-1,0
       0      .1       0   191.9    .045       0   229.2      .1       0
Bank Sta=191.9,229.2
XS Rating Curve= 0 ,0
Exp/Cntr(USF)=0,0
Exp/Cntr=0.3,0.1

Type RM Length L Ch R = 1 ,18573   ,301,300.2,296.7
XS GIS Cut Line= 6
1607921.54682025468357.3778875021607953.92011508468439.102461591
1607978.78358242468509.9645245821608012.87373734468604.008955926
1608039.13188693468674.2378180921608072.37788342468755.226173177
#Sta/Elev= 30
       0  862.16    10.2  853.92    38.4  833.45    56.1  826.87    73.7  815.41
    77.2  814.35    91.3  812.57   108.7  808.76     163  799.56   176.8  794.63
   184.4  789.04     187   787.8   200.4786.4553   206.2  785.45   225.3  785.22
   230.5  785.53     233 786.424   237.6  789.13   241.1  790.45   259.2  791.94
   284.2  802.12   300.6  806.91   321.6  809.55   335.2  812.36   352.9  814.29
   367.9  818.97     378  820.93     395  825.56   405.7  830.06   425.6  832.67
#Mann= 3 ,-1,0
       0      .1       0   200.4    .045       0     233      .1       0
Bank Sta=200.4,233
XS Rating Curve= 0 ,0
Exp/Cntr(USF)=0,0
Exp/Cntr=0.3,0.1

Type RM Length L Ch R = 1 ,18273   ,308.3,300.3,284
XS GIS Cut Line= 6
1607635.24424326468511.2883408371607675.84488384468588.798684508
 1607710.6450111468655.2362156661607757.04583693468743.819371834
1607791.84596418468810.2569030081607832.44660476468887.766918585
#Sta/Elev= 30
       0  889.82     3.6  885.15    11.4  878.01    18.4  866.59    33.2   849.5
    54.5  830.21      60   826.4    74.6  821.18    92.5   811.6   118.3  802.99
   151.8  798.68   159.2  796.15   170.3  790.75   183.9  786.82   189.8783.6733
   195.9   782.8   222.1  782.49   234.8783.6711   240.6  784.49     252  789.05
     274  790.94   281.2  794.17   292.5  800.92   307.3  806.23   325.8  808.42
   351.8  808.29   366.6  810.16   392.5   815.8   403.6  820.37     425  832.89
#Mann= 3 ,-1,0
       0      .1       0   189.8    .045       0   234.8      .1       0
Bank Sta=189.8,234.8
XS Rating Curve= 0 ,0
Exp/Cntr(USF)=0,0
Exp/Cntr=0.3,0.1

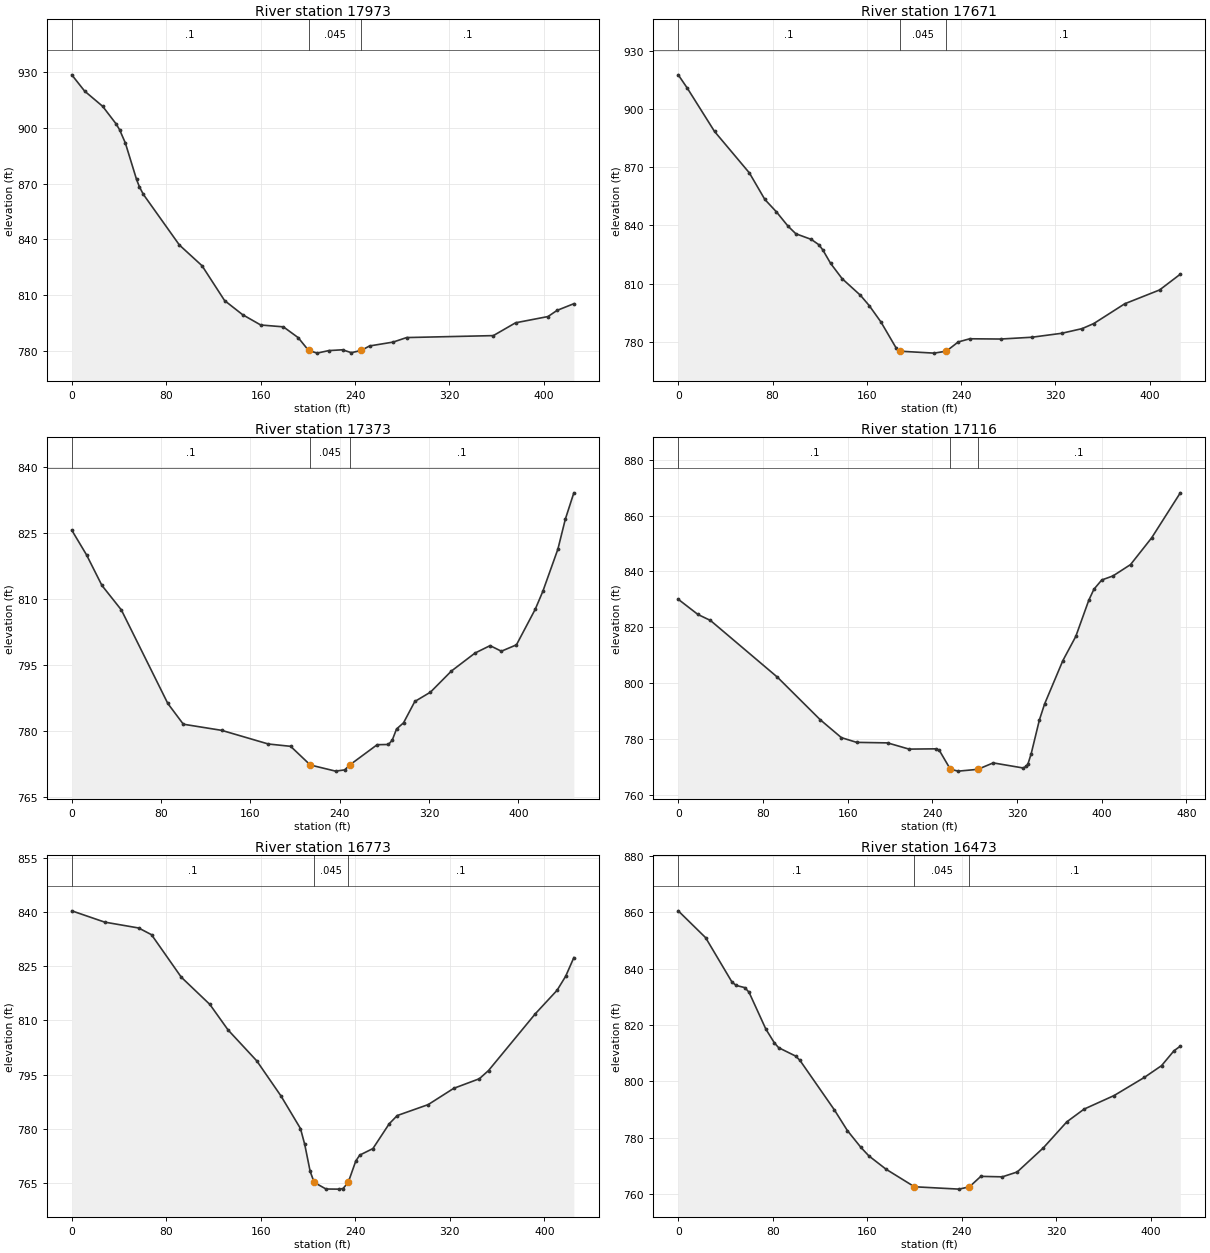
Type RM Length L Ch R = 1 ,17973   ,309.5,301.4,287.5
XS GIS Cut Line= 6
1607313.24193451468766.7117145061607388.27262434468811.729997173
1607452.58450359468850.3171903341607538.00165559468902.320367172
1607600.06157084468944.6611617511607671.87966867468995.033436343
#Sta/Elev= 30
       0  928.65    10.9  919.89    26.2  911.68    37.7  902.11    40.6  898.97
    45.4  891.94    54.9   872.3    57.3  868.36    60.6  864.33    91.2     837
   110.4  825.83   129.5  807.08   144.8  799.47   160.1  793.94   179.3  792.94
   191.8  787.15   200.6780.2847   207.9  778.79   217.7  780.15   229.4  780.59
   236.9  779.02   245.2780.2313   252.3  782.65   272.3  784.74   283.7  787.17
   357.2  788.22     376  795.12   403.5  798.49   411.2  801.81   425.4   805.4
#Mann= 3 ,-1,0
       0      .1       0   200.6    .045       0   245.2      .1       0
Bank Sta=200.6,245.2
XS Rating Curve= 0 ,0
Exp/Cntr(USF)=0,0
Exp/Cntr=0.3,0.1

Type RM Length L Ch R = 1 ,17671   ,304.5,298.2,294.1
XS GIS Cut Line= 6
1607222.88876876469166.3765975831607310.71602093469163.410068095
1607386.00491235469161.5793630931607486.01816376469164.707309589
1607560.89465442469169.0563822541607648.58772051469165.333292589
#Sta/Elev= 30
       0  917.57     7.8  910.61    30.8  888.41    60.4  867.03    73.5  853.38
    83.3  847.01    93.2  839.61    99.8  835.73   112.9  832.82   119.4  830.04
   122.7  827.38   129.3  820.46   139.1  812.58   154.6  804.04   162.1   798.7
     172  790.29   185.1  776.68   188.2775.2507   217.1  774.26   227.5775.2711
   237.6  780.03   247.4  781.65   273.7  781.52     300  782.44   325.4  784.48
   342.7  786.88   352.6   789.5   378.9  799.69   408.4  806.79     426  814.91
#Mann= 3 ,-1,0
       0      .1       0   188.2    .045       0   227.5      .1       0
Bank Sta=188.2,227.5
XS Rating Curve= 0 ,0
Exp/Cntr(USF)=0,0
Exp/Cntr=0.3,0.1

Type RM Length L Ch R = 1 ,17373   ,230.8,257.4,271.7
XS GIS Cut Line= 6
1607283.88733442469428.9521879261607388.72800401469464.939320669
1607464.82102767469460.5535026791607562.16269651469437.650005177
 1607635.1687841469420.4715618341607720.34315443469400.431247592
#Sta/Elev= 30
       0  825.62    13.2  820.01      27  813.05    44.4  807.48      86  786.21
    99.9  781.49   134.3  780.09     176  776.99     196  776.46   213.6 772.215
   236.2  770.82   244.4   771.1   248.8772.1988   273.5  776.83   283.6  776.88
     287  777.88   290.8  780.39   297.1  781.81   307.2  786.66   321.2  788.78
   339.9  793.57   361.1  797.67   374.6  799.36   384.7  798.09   398.2  799.54
   415.1  807.67   421.8  811.69   435.3  821.29     442  828.14   449.6  834.11
#Mann= 3 ,-1,0
       0      .1       0   213.6    .045       0   248.8      .1       0
Bank Sta=213.6,248.8
XS Rating Curve= 0 ,0
Exp/Cntr(USF)=0,0
Exp/Cntr=0.3,0.1

Type RM Length L Ch R = 1 ,17116   ,341.3,342.6,341.7
XS GIS Cut Line= 3
1607228.77214322469481.410146607 1607419.0395812469613.380742221
1607525.41282709469831.489937245
#Sta/Elev= 30
       0     830    18.6  824.55    30.4  822.41    93.7  802.07   134.1  786.83
   154.1  780.41   168.5  778.72   197.7  778.53     218   776.3   243.5   776.4
   246.4  775.97   257.1769.0409   264.6  768.41   282.9  769.05   297.5  771.36
   325.9  769.53   328.9  770.21   330.3  770.97   333.4  774.71   341.1  786.74
     346  792.46   363.3  808.05   375.5   816.7   387.7   829.6   392.6  833.59
     400  836.91   410.6  838.36   427.2  842.43   447.1  851.99   474.2  868.14
#Mann= 3 ,-1,0
       0      .1       0   257.1    .045       0   282.9      .1       0
Bank Sta=257.1,282.9
XS Rating Curve= 0 ,0
Exp/Cntr(USF)=0,0
Exp/Cntr=0.3,0.1

Type RM Length L Ch R = 1 ,16773   ,299.7,300,300.5
XS GIS Cut Line= 6
1607031.43049026469568.5532866721607067.63842309469648.210607678
1607098.67379409469716.4877020871607140.05363259469807.524593502
1607171.08867551469875.8023440841607209.49575092469954.459667087
#Sta/Elev= 30
       0  840.33    27.8  837.21    56.6  835.58    67.5  833.72    92.7  821.96
   116.9  814.41   132.3  807.35   156.6  798.79   177.1  789.07   193.6  780.05
   197.2  775.66   201.8  768.18   205.2  765.15   215.2  763.31     226  763.28
   229.6  763.44     234  765.13   240.4  771.05   243.8  772.71   254.9   774.5
   268.7  781.37   275.5  783.65   301.7  786.68   323.3  791.18     345  793.84
   352.8  796.12   392.5  811.87   410.8  818.33   418.1  822.23     425  827.38
#Mann= 3 ,-1,0
       0      .1       0   205.2    .045       0     234      .1       0
Bank Sta=205.2,234
XS Rating Curve= 0 ,0
Exp/Cntr(USF)=0,0
Exp/Cntr=0.3,0.1

Type RM Length L Ch R = 1 ,16473   ,313.6,300,278.5
XS GIS Cut Line= 6
1606769.44446567469716.1786475931606804.60187568469796.368775919
  1606837.205485469863.9112917481606880.67718284469953.967870176
1606913.28079218470021.5107140841606951.31943001470100.309769094
#Sta/Elev= 30
       0  860.51    23.2  850.98    45.6  835.18    49.2  834.03    56.3  833.27
    59.9  831.66    74.2  818.54    81.4  813.67      85  811.96    99.5  808.96
   103.1  807.43   132.3  789.83   143.2  782.56   154.6  776.62   161.4  773.57
     176  768.83     200762.6163   237.8  761.78   246.6762.6176   256.2  766.31
   274.4  766.14     287  767.86   309.1  776.41     329  785.65   343.6  790.16
   369.1  794.99   394.6   801.4   409.2  805.58   419.7  810.84   425.1   812.5
#Mann= 3 ,-1,0
       0      .1       0     200    .045       0   246.6      .1       0
Bank Sta=200,246.6
XS Rating Curve= 0 ,0
Exp/Cntr(USF)=0,0
Exp/Cntr=0.3,0.1

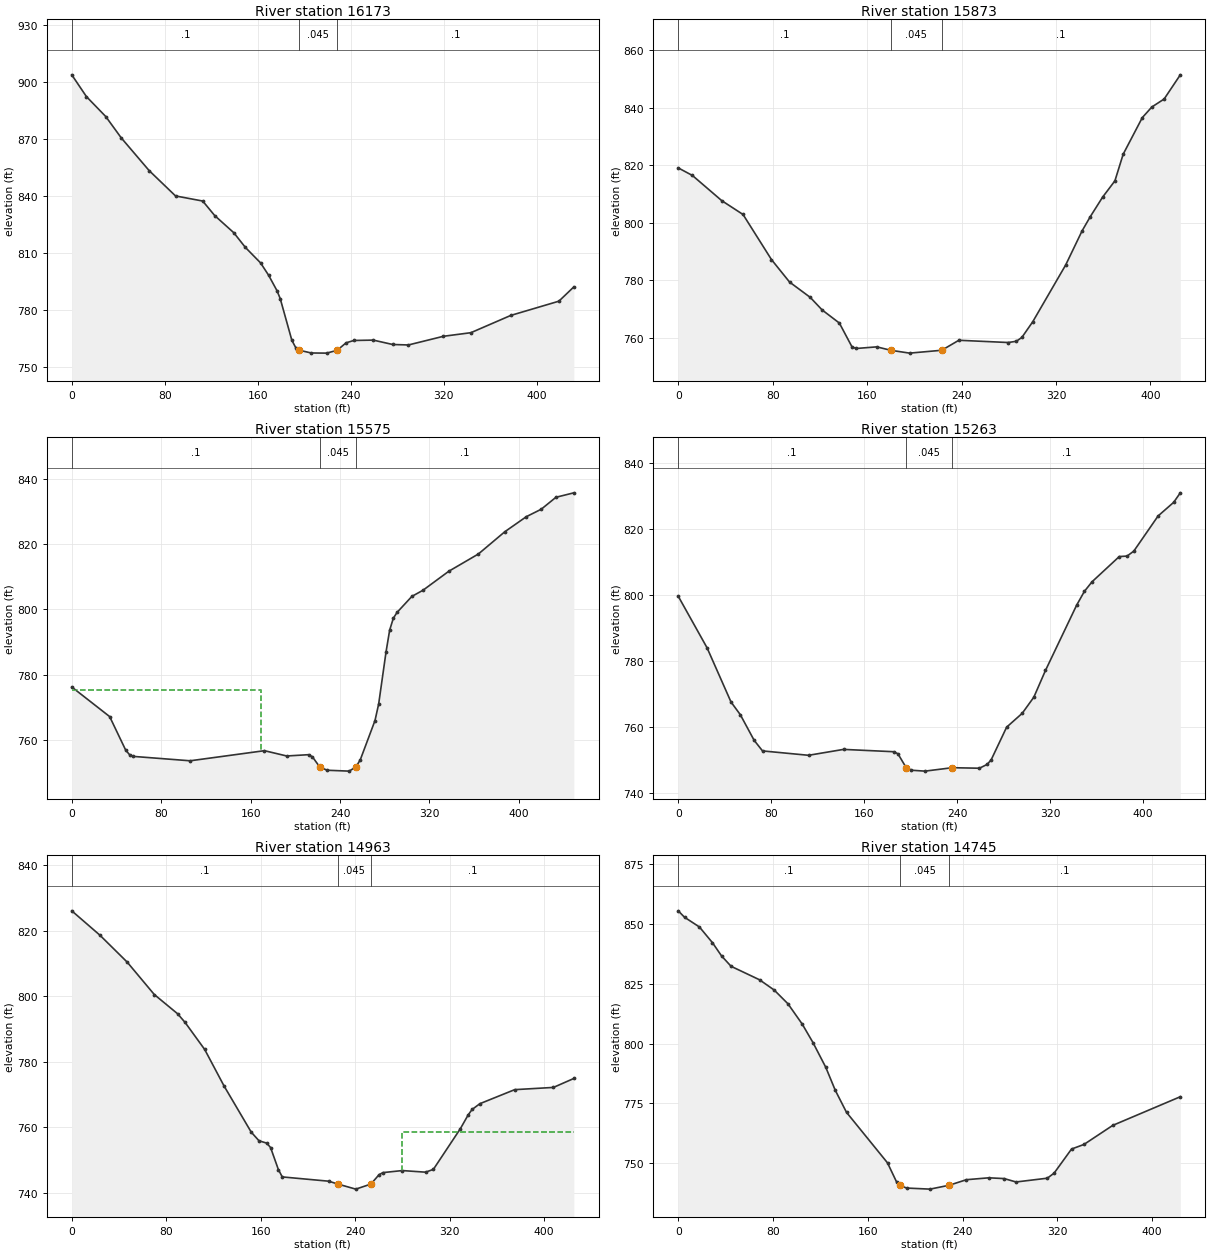
Type RM Length L Ch R = 1 ,16173   ,309.5,300,291.7
XS GIS Cut Line= 6
1606447.32043801470073.3147443381606533.38194567470089.115893841
 1606607.1488585470102.6601580831606705.50463292470120.718520924
1606778.81747842470136.735221177 1606869.0502376470164.940873429
#Sta/Elev= 30
       0  903.87    12.6  892.41    29.3  881.85    42.6  870.62    66.6  853.39
    89.3  840.04   112.7  837.35     123   829.7   139.4  820.67   149.4  812.92
   162.5  804.74   169.4  798.24   176.6  790.12   179.4  785.93   189.4  763.98
   192.8  760.01   195.8758.7123   206.1  757.27   219.4  757.19   228.4758.6886
   236.1  762.63   242.8  763.86   259.5  764.05   276.2  761.74   289.7  761.49
   319.9  766.07   343.5  767.96   377.9  777.08   419.2  784.56   432.1   792.1
#Mann= 3 ,-1,0
       0      .1       0   195.8    .045       0   228.4      .1       0
Bank Sta=195.8,228.4
XS Rating Curve= 0 ,0
Exp/Cntr(USF)=0,0
Exp/Cntr=0.3,0.1

Type RM Length L Ch R = 1 ,15873   ,293,298,301.9
XS GIS Cut Line= 6
1606527.78221934470475.0101351741606607.91887009470439.137175426
1606677.79438651470411.7622301731606772.12720309 470378.57627292
1606842.87673351470353.6865589171606925.41790701470324.648559257
#Sta/Elev= 30
       0  819.09      12  816.46    36.9  807.69    54.9  802.89      79   787.2
    94.3   779.4   111.8  774.08   121.9   769.7   136.5  765.14   147.1  756.94
   150.6   756.3   168.2  756.87     180755.6814     196  754.69   223.2755.6854
   237.7  759.16   279.5  758.38   286.4  758.81   291.1  760.16   300.3   765.6
   328.2  785.34   342.1   797.2     349  802.11   359.5  808.94   369.9  814.59
   376.9  823.85   393.1  836.57   401.2  840.27   411.6  843.04   425.3  851.45
#Mann= 3 ,-1,0
       0      .1       0     180    .045       0   223.2      .1       0
Bank Sta=180,223.2
XS Rating Curve= 0 ,0
Exp/Cntr(USF)=0,0
Exp/Cntr=0.3,0.1

Type RM Length L Ch R = 1 ,15575   ,282.5,312,333.7
XS GIS Cut Line= 6
1606569.87301442470631.6853467521606669.23305193470676.385716677
1606746.13939418470687.5854974241606845.88689809470679.463466421
1606920.34180167470670.4385500851607007.20612925470659.909699753
#Sta/Elev= 30
       0  776.28    33.9  767.23    48.3  756.94    51.9  755.51    54.8  755.07
   105.9  753.72   172.4  756.81   192.3  755.19     212  755.59   215.3  754.93
   221.9  751.81   228.5  750.83   248.2  750.56   254.2751.8455   258.1     754
   271.3  766.03   274.6  771.13   281.2  787.07   284.4  793.65   287.7   797.3
     291  799.07   304.3  803.98   314.2  805.85   337.3  811.66   363.8  816.94
   387.5  823.76   406.7  828.35     420  830.62   433.2  834.28   449.2  835.64
#Mann= 3 ,-1,0
       0      .1       0   221.9    .045       0   254.2      .1       0
#XS Ineff= 2 , 0
          169.02  775.41
Permanent Ineff=
       F       F
Bank Sta=221.9,254.2
XS Rating Curve= 0 ,0
Exp/Cntr(USF)=0,0
Exp/Cntr=0.3,0.1

Type RM Length L Ch R = 1 ,15263   ,295.7,299.6,302.2
XS GIS Cut Line= 6
1606520.06799592470667.3877031651606569.62334301470747.790429503
1606583.87462685470821.4238124191606602.87655734470919.602093756
 1606617.1275131470993.2354766731606633.74624626471079.142785177
#Sta/Elev= 30
       0  799.59    24.8  783.95    45.4  767.52    53.4  763.67    65.3   755.9
    72.5  752.69   112.1  751.36   142.2  753.15   185.6  752.44     189  751.81
   196.1747.6033   200.2  746.84   212.3  746.56   235.7   747.6   259.1  747.44
   265.8  748.61   269.2  749.99   282.5  759.89   295.9  764.09   305.9  768.98
   315.9  777.08   342.7  796.86   349.4  801.07     356  803.98   379.4  811.62
   386.1  811.76   391.9  813.27   412.8  823.93   426.2  828.06   431.9  830.94
#Mann= 3 ,-1,0
       0      .1       0   196.1    .045       0   235.7      .1       0
Bank Sta=196.1,235.7
XS Rating Curve= 0 ,0
Exp/Cntr(USF)=0,0
Exp/Cntr=0.3,0.1

Type RM Length L Ch R = 1 ,14963   ,228,218.4,203.9
XS GIS Cut Line= 6
1606308.08154325470669.138027757 1606302.8778135470756.637852758
1606298.69639142470831.6380308421606296.55958468470931.638158917
1606294.10617751471006.5894525951606291.24496275471094.011849925
#Sta/Elev= 30
       0   826.1    23.8  818.67    46.9  810.45    69.9  800.53    89.6  794.67
      96     792   112.6  783.74     129  772.59     152   758.5   158.6  755.85
   165.1  755.14   168.4  753.79     175  747.07   178.3  744.81   217.7   743.5
   225.4742.6275   240.6  741.08   253.4742.6263   260.3   745.5   263.6  746.13
     280  746.75   299.7  746.26   306.3  747.11   329.2  759.56   335.8  763.76
   339.1  765.41   345.7  767.18   375.2  771.47     408  772.15   425.3  774.89
#Mann= 3 ,-1,0
       0      .1       0   225.4    .045       0   253.4      .1       0
#XS Ineff= 2 , 0
                          280.14          758.41
Permanent Ineff=
       F       F
Bank Sta=225.4,253.4
XS Rating Curve= 0 ,0
Exp/Cntr(USF)=0,0
Exp/Cntr=0.3,0.1

Type RM Length L Ch R = 1 ,14745   ,218.8,209.4,199.5
XS GIS Cut Line= 4
1605970.53578014470781.0345956631606062.44948049470912.980033395
1606156.02490762471045.3089202341606189.75828908 471140.31195417
#Sta/Elev= 30
       0  855.52     5.3  852.84    17.9  848.76    28.9  842.19    36.6  836.64
    44.6  832.33    68.6   826.7      81   822.4    92.6  816.66   104.6   808.2
   113.7  800.46   124.5  790.12   132.5  780.53     142  771.29   176.6  750.17
   184.4  742.04   186.8  740.83   192.7  739.64   212.5  739.19   228.8  740.83
   243.2  743.13   262.1  743.92     275   743.6   285.1  742.18   311.5  743.76
   317.2  745.88   331.9  755.94   342.4  757.87   366.7  765.84   423.7  777.81
#Mann= 3 ,-1,0
       0      .1       0   186.8    .045       0   228.8      .1       0
Bank Sta=186.8,228.8
XS Rating Curve= 0 ,0
Exp/Cntr(USF)=0,0
Exp/Cntr=0.3,0.1

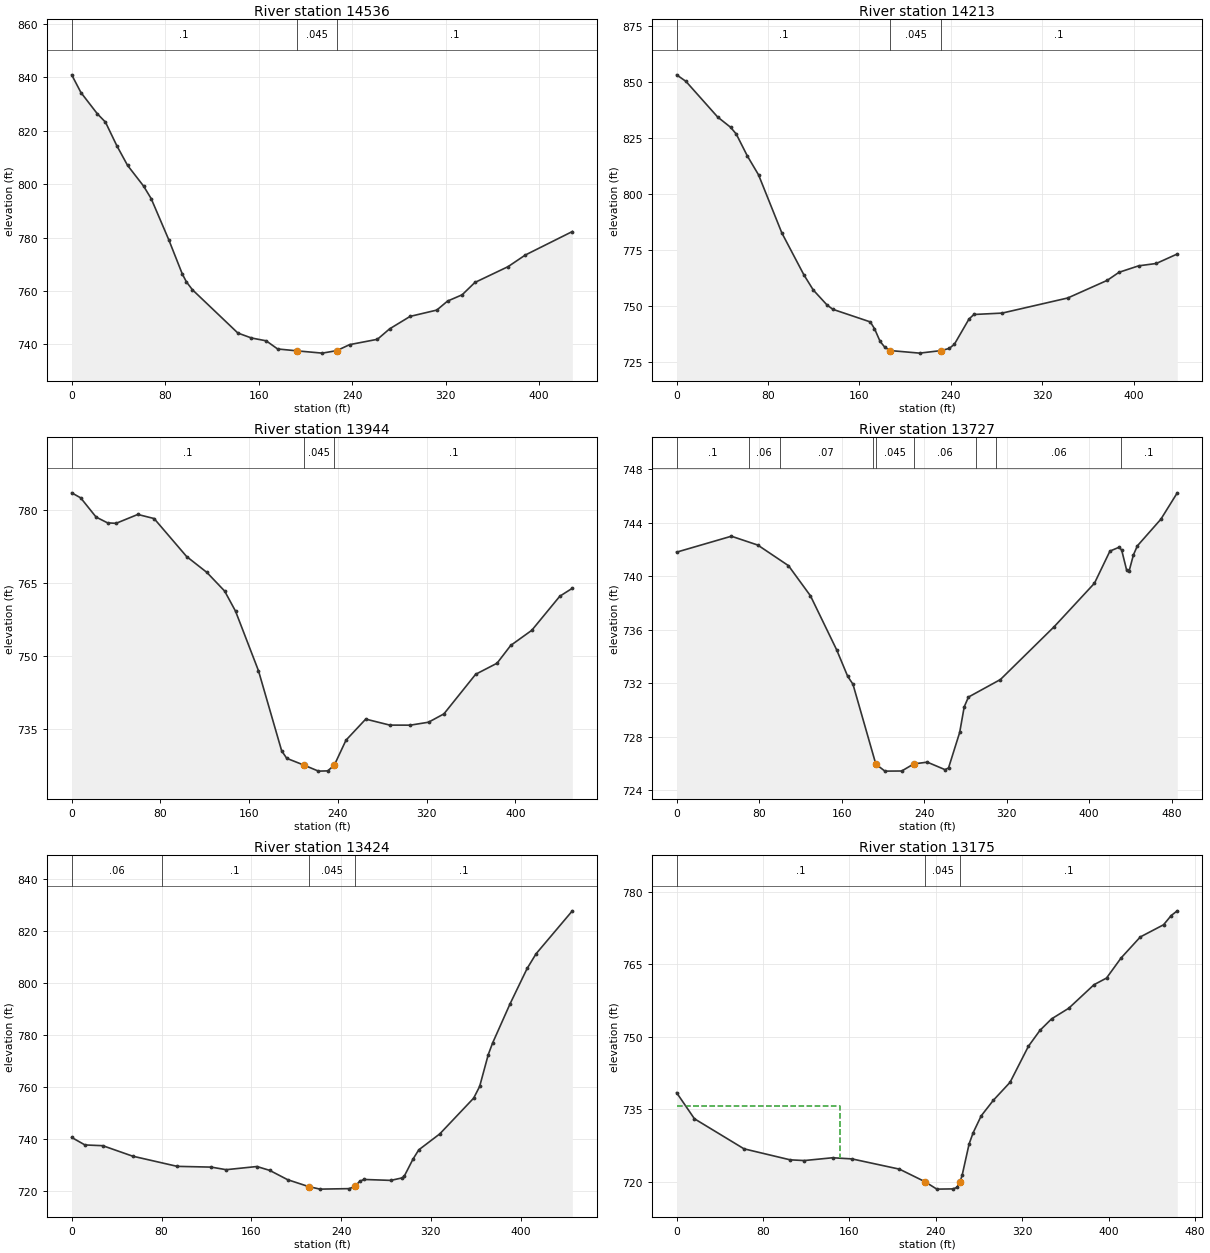
Type RM Length L Ch R = 1 ,14536   ,312.2,322.8,326.4
XS GIS Cut Line= 3
1605805.35335749470962.1307627921605911.21646696471085.952792621
1606151.29887594471199.377552769
#Sta/Elev= 30
       0  840.92     7.9  834.29    21.9  826.35    28.9   823.2    38.6  814.38
    47.8  807.01    61.5  799.26      68  794.57    83.1  779.12    94.7  766.27
    98.2  763.36   103.3  760.43   142.2  744.22   153.8  742.37   166.4  741.31
   176.2  738.26   192.6  737.56   214.4   736.7  226.87  737.64   237.8  739.88
   261.6  741.88     272  745.78   289.6  750.46   312.4  752.82   321.6  756.19
   334.1  758.55     345  763.16   373.4  769.09   388.1  773.43   428.4  782.24
#Mann= 3 ,-1,0
       0      .1       0   192.6    .045       0  226.87      .1       0
Bank Sta=192.6,226.87
XS Rating Curve= 0 ,0
Exp/Cntr(USF)=0,0
Exp/Cntr=0.3,0.1

Type RM Length L Ch R = 1 ,14213   ,271.7,269.4,266.1
XS GIS Cut Line= 6
1605604.56974716471149.5483635921605669.54074582471221.377944346
1605720.38644466471281.6668657621605785.46571083471357.592238839
1605834.27499641471414.5366787571605891.21910825471480.971585255
#Sta/Elev= 30
       0   853.4     8.1  850.51      36  834.53    47.2  830.01    52.2  826.97
    61.9  817.19    71.7  808.76    92.1  782.82   111.4  764.11   119.6  757.35
   131.7  750.63   136.8  748.71   169.5   743.1   173.2  740.09   178.1   734.4
   182.4  731.68   187.1   730.3   212.7  729.16   231.6   730.3   238.6  731.26
   243.1   733.1   255.9  744.38   260.2  746.41   284.9  747.03   342.3  753.77
   376.9  761.65   387.2  765.24   404.4  768.13   419.8  769.18   438.2  773.42
#Mann= 3 ,0,0
       0      .1       0   187.1    .045       0   231.6      .1       0
Bank Sta=187.1,231.6
XS Rating Curve= 0 ,0
Exp/Cntr(USF)=0,0
Exp/Cntr=0.3,0.1

Type RM Length L Ch R = 1 ,13944   ,214.2,216.8,218.7
XS GIS Cut Line= 6
1605395.75444657471351.8005242941605460.67065533471410.470026388
1605516.31326057471460.7583116291605590.50340091471527.809358626
1605646.14600615471578.0973158031605743.58998102471637.078819886
#Sta/Elev= 30
       0  783.46     8.1  782.43      22  778.49    32.3  777.31      40  777.21
    59.6  779.03    74.3  778.19   103.6  770.41   121.9  767.15   137.9  763.33
   147.7  759.22   168.4  747.01   189.3   730.6   193.9  729.06   209.2  727.69
   222.5  726.44   230.8  726.49  236.76  727.66   247.3  732.78   265.1   737.1
   286.8  735.87   305.4  735.86   321.7  736.46   335.6  738.17   364.2  746.28
   383.5  748.55   395.8  752.19   414.8  755.29   440.1  762.28   451.4  763.91
#Mann= 3 ,-1,0
       0      .1       0   209.2    .045       0  236.76      .1       0
Bank Sta=209.2,236.76
XS Rating Curve= 0 ,0
Exp/Cntr(USF)=0,0
Exp/Cntr=0.3,0.1

Type RM Length L Ch R = 1 ,13727   ,299.7,302.9,303.3
XS GIS Cut Line= 3
1605271.39660875471488.5763495121605469.33662653471728.085802373
1605620.49483992471815.777453862
#Sta/Elev= 30
       0  741.79    53.1  742.98    78.7  742.32   108.5  740.78   129.8  738.53
   155.3  734.48   165.9  732.52     171  731.93   193.2725.9611     202  725.44
   218.3  725.45     230  725.98   243.1  726.11   260.3  725.55   263.7  725.68
   274.5  728.33   278.9  730.24     283  730.97     314  732.28   366.2  736.23
   405.2  739.47   420.2  741.87   429.2  742.16   431.6  741.94   436.4  740.45
   438.8  740.38     443  741.59   446.8  742.26   469.6  744.25   485.5  746.22
#Mann= 9 ,-1,0
       0      .1       0      70     .06       0     100     .07       0
     190     .06       0   193.2    .045       0     230     .06       0
     290     .07       0     310     .06       0  430.72      .1       0
Bank Sta=193.2,230
XS Rating Curve= 0 ,0
Exp/Cntr(USF)=0,0
Exp/Cntr=0.3,0.1

Type RM Length L Ch R = 1 ,13424   ,221.7,249.3,260.8
XS GIS Cut Line= 5
1605102.06285991471617.0618723431605129.99974428471777.835673012
1605198.45103346471876.4308787751605240.55527996471938.553786026
1605287.01745737472012.974240871
#Sta/Elev= 30
       0   740.7    11.8  737.82    27.7  737.53    54.3   733.5      94  729.58
   124.3  729.29   137.6   728.3     165  729.52   176.4  728.03   192.4  724.44
     211  721.81   221.2  720.82   247.2  721.01   252.1 721.835   256.6  723.84
   260.3  724.54   284.3  724.18   294.3  725.14   296.2  725.76   304.1  732.42
   309.2  735.94   327.9  742.07   358.1  755.84   363.4  760.32   371.1   772.6
     375  777.09   390.5  792.11   405.7  805.71   413.7  811.38     446  827.89
#Mann= 4 ,-1,0
       0     .06       0      80      .1       0     211    .045       0
   252.1      .1       0
Bank Sta=211,252.1
XS Rating Curve= 0 ,0
Exp/Cntr(USF)=0,0
Exp/Cntr=0.3,0.1

Type RM Length L Ch R = 1 ,13175   ,336.6,321.5,300.1
XS GIS Cut Line= 5
1605009.53036504471680.3832385231605009.76515432471829.866951368
 1604937.2371721471962.8480387631604907.53578793472031.716011256
1604872.88362625472112.062307253
#Sta/Elev= 30
       0  738.41    16.5  733.01    62.4  726.78   105.1   724.5   118.2  724.35
   144.4  724.93   162.4  724.69   206.3  722.57   229.8719.9843   240.9  718.43
   255.8  718.48   259.6  718.78   262.4719.9443   264.4  721.36   270.8   727.8
   274.5   730.1     282  733.62   293.2  736.83   308.7  740.56   325.7  748.03
   336.4  751.33   347.1   753.7     363   755.9   386.4  760.78     398  762.16
   411.5  766.33   429.3  770.68   450.8   773.2   457.9  775.12   463.5  776.09
#Mann= 3 ,-1,0
       0      .1       0   229.8    .045       0   262.4      .1       0
#XS Ineff= 2 , 0
          151.62  735.67
Permanent Ineff=
       F       F
Bank Sta=229.8,262.4
XS Rating Curve= 0 ,0
Exp/Cntr(USF)=0,0
Exp/Cntr=0.3,0.1

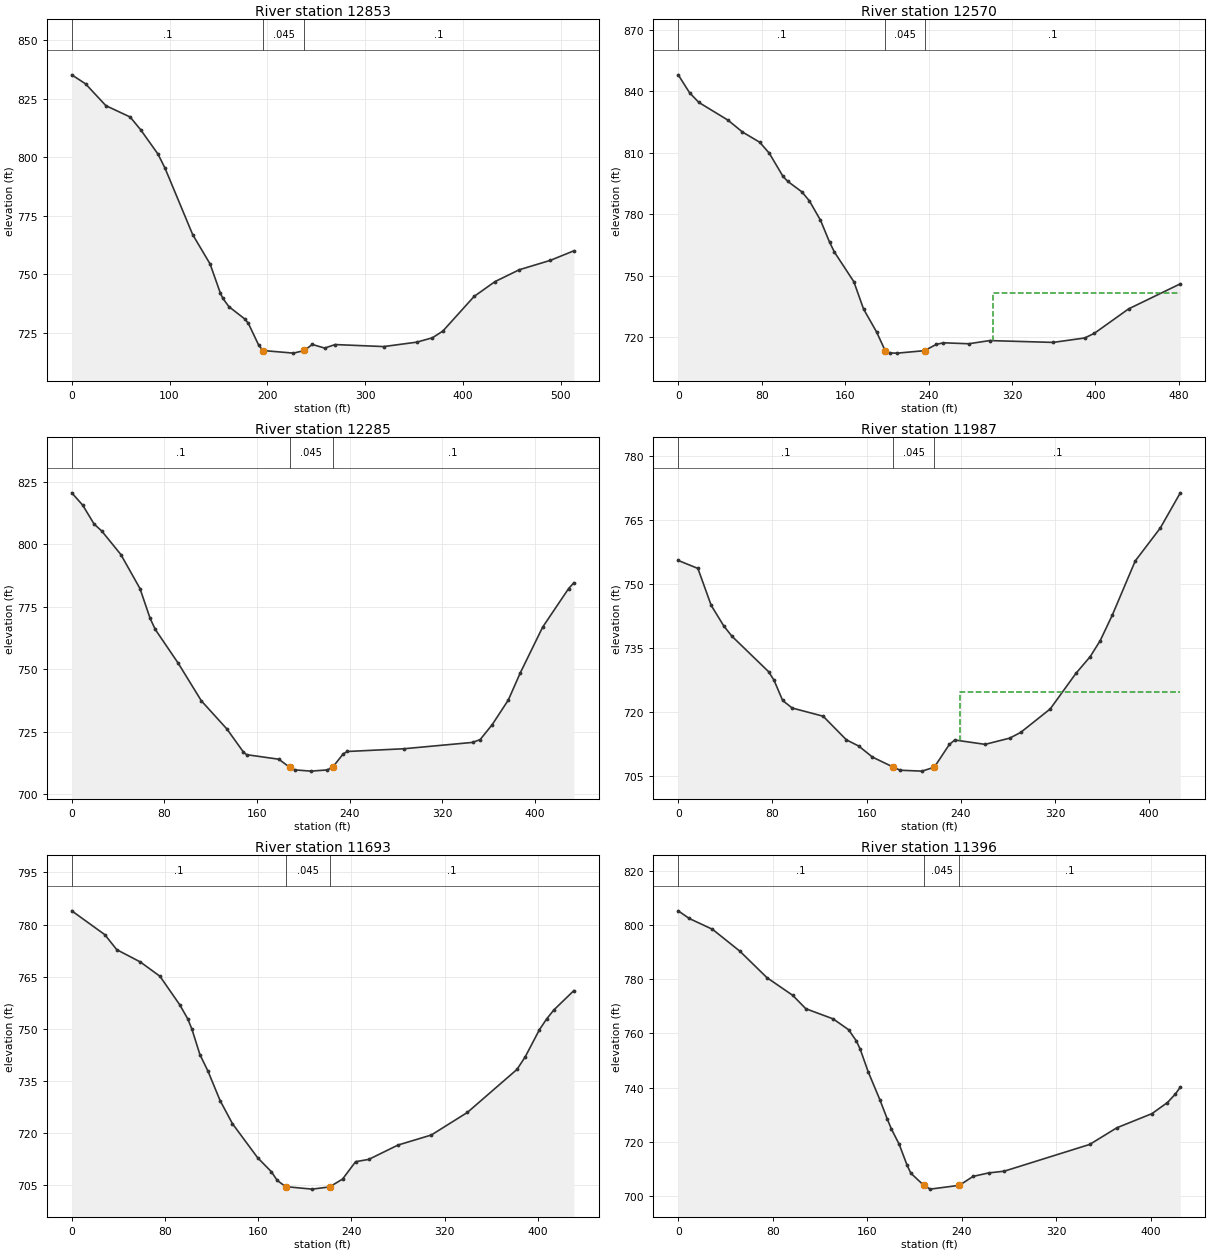
Type RM Length L Ch R = 1 ,12853   ,289.5,283.1,272.3
XS GIS Cut Line= 2
  1604600.123345471631.8824933321604797.48096775472106.017814942
#Sta/Elev= 30
       0  835.16    14.1  831.31    34.9  821.99    59.7  817.15    70.4  811.74
    88.2  801.31    95.3  795.38   123.7   766.9   141.5  754.37   152.1  741.81
   154.6  739.66   160.7  736.16     177  730.87   180.6  729.04   191.2  719.71
   195.5717.4032   226.8  716.29     238717.4167     246     720   258.7  718.45
   269.4  719.95   319.1  719.09   352.9  720.98   368.9  722.84   379.6   725.7
   411.5  740.48   432.9  746.83   457.7  751.89   489.7  755.94   513.6  759.99
#Mann= 3 ,-1,0
       0      .1       0   195.5    .045       0     238      .1       0
Bank Sta=195.5,238
XS Rating Curve= 0 ,0
Exp/Cntr(USF)=0,0
Exp/Cntr=0.3,0.1

Type RM Length L Ch R = 1 ,12570   ,290.2,285.3,274.6
XS GIS Cut Line= 5
1604292.97829001471834.2839914261604357.04673143471893.878688499
1604411.96230401471944.9596230831604485.18328618472013.067098424
1604657.19240419472148.415367935
#Sta/Elev= 30
       0  848.12    10.9  839.34    19.8  834.63    47.7  825.98    61.6  820.18
    78.1   815.2    87.3  809.83   100.5  798.47     105  796.07   118.5  790.97
   125.8  786.51   136.4  777.08   145.1  766.38   149.8  761.49   168.4  747.03
   177.7  733.69   190.1  722.59   198.4 713.376   202.9  712.22   210.2  712.16
   236.2  713.37   247.3   716.4   254.3  717.21   278.6  716.74   298.6  718.29
   359.4   717.4   389.8  719.56   399.1  721.89   431.8  733.77   481.4  746.02
#Mann= 3 ,-1,0
       0      .1       0   198.4    .045       0   236.2      .1       0
#XS Ineff= 2 , 0
                          302.17          741.68
Permanent Ineff=
       F       F
Bank Sta=198.4,236.2
XS Rating Curve= 0 ,0
Exp/Cntr(USF)=0,0
Exp/Cntr=0.3,0.1

Type RM Length L Ch R = 1 ,12285   ,289.7,297.4,302.4
XS GIS Cut Line= 6
1604157.16392909472195.6854995941604249.75462317472206.156279176
1604326.47756684 472219.418063671604420.86254868472252.455071092
1604491.65177718472277.2315963361604574.23921043472306.137706503
#Sta/Elev= 30
       0  820.67     9.4  815.75    19.3  808.15    25.9  805.36    42.4  795.93
    58.9   782.3    67.6  770.42    72.1  765.92    91.9  752.39   111.9   737.3
     134  725.99   148.2  716.78     151  715.72   178.8   713.9   188.2  710.64
   192.7  709.62   206.6  709.13   220.5  709.61   225.2710.6577   234.4  716.07
   237.9     717   286.8   718.1     346  720.64   352.6  721.77     363  727.76
   376.9  737.62   387.3  748.56   406.6  766.87     429  782.31   433.5  784.62
#Mann= 3 ,-1,0
       0      .1       0   188.2    .045       0   225.2      .1       0
Bank Sta=188.2,225.2
XS Rating Curve= 0 ,0
Exp/Cntr(USF)=0,0
Exp/Cntr=0.3,0.1

Type RM Length L Ch R = 1 ,11987   ,296.4,293.7,290.6
XS GIS Cut Line= 6
 1604075.9295115472358.0582063351604140.66855526472418.576129928
1604196.77244568472468.8795070051604273.96487659472532.450902179
1604331.85944584472580.129284501  1604399.403274 472635.75384517
#Sta/Elev= 30
       0  755.44    16.7  753.57      28   744.9    38.6  740.12    45.5   737.7
    76.7  729.37    81.4  727.33    88.7   722.6    96.8  720.83   123.1  718.91
   142.8  713.38   153.4   711.9     165  709.32   182.8 706.954   188.5  706.24
     207  706.03   217.5706.9464   230.3  712.28   234.9  713.33   260.7  712.31
   281.6  713.77   290.9  715.11     316  720.62   337.8  728.95     350   732.9
   358.5  736.66   368.8  742.67   388.2  755.32   409.5  763.05   426.5   771.3
#Mann= 3 ,-1,0
       0      .1       0   182.8    .045       0   217.5      .1       0
#XS Ineff= 2 , 0
                          239.71          724.55
Permanent Ineff=
       F       F
Bank Sta=182.8,217.5
XS Rating Curve= 0 ,0
Exp/Cntr(USF)=0,0
Exp/Cntr=0.3,0.1

Type RM Length L Ch R = 1 ,11693   ,304.1,297.7,284.5
XS GIS Cut Line= 6
1603922.32909693472690.0454032571604010.75706968472711.909860834
1604083.91046667472736.3743788451604171.77019909472784.478613332
1604235.37046559472824.2282057551604309.56979226472870.603441089
#Sta/Elev= 30
       0  783.94    28.4  777.07    38.6  772.76    58.8  769.23    75.7   765.1
    92.7  756.88    99.6  752.81   103.1  749.89     110  742.55   116.9  737.79
   127.3  729.33   137.9  722.67   159.5  712.88   171.4   708.8   176.3  706.35
   183.5  704.55   206.2  703.83   221.2  704.46   232.4  706.72   243.6  711.73
   254.9  712.39     280  716.52   308.6  719.41   339.5   725.9   382.1  738.29
   389.1  741.87   401.4  749.75   407.6  752.84   413.8  755.43   430.9  760.97
#Mann= 3 ,-1,0
       0      .1       0   183.5    .045       0   221.2      .1       0
Bank Sta=183.5,221.2
XS Rating Curve= 0 ,0
Exp/Cntr(USF)=0,0
Exp/Cntr=0.3,0.1

Type RM Length L Ch R = 1 ,11396   ,301.3,302.5,301.5
XS GIS Cut Line= 6
1603825.86406675473051.8645614981603913.07616268 473044.77304025
1603987.82962209 473038.694312261604087.50068259473030.589341596
1604162.25381392 473024.510613591604249.46590984473017.418764248
#Sta/Elev= 30
       0  805.27     9.3  802.45      29  798.45    52.1   790.4    75.1   780.6
    96.9  774.08     108  769.13   131.1  765.39   144.2  761.39   150.8  757.24
   154.1  754.12   160.7  745.96   170.6  735.62   177.1  728.27   180.4  724.77
     187  719.12   193.6  711.51   196.9  708.42   207.8703.9615   213.3  702.54
     238703.9552   249.6  707.24   262.7  708.52   275.9  709.16   348.3  719.04
   371.3  725.19     401  730.41   414.1   734.5   420.7  737.58     425  740.21
#Mann= 3 ,-1,0
       0      .1       0   207.8    .045       0     238      .1       0
Bank Sta=207.8,238
XS Rating Curve= 0 ,0
Exp/Cntr(USF)=0,0
Exp/Cntr=0.3,0.1