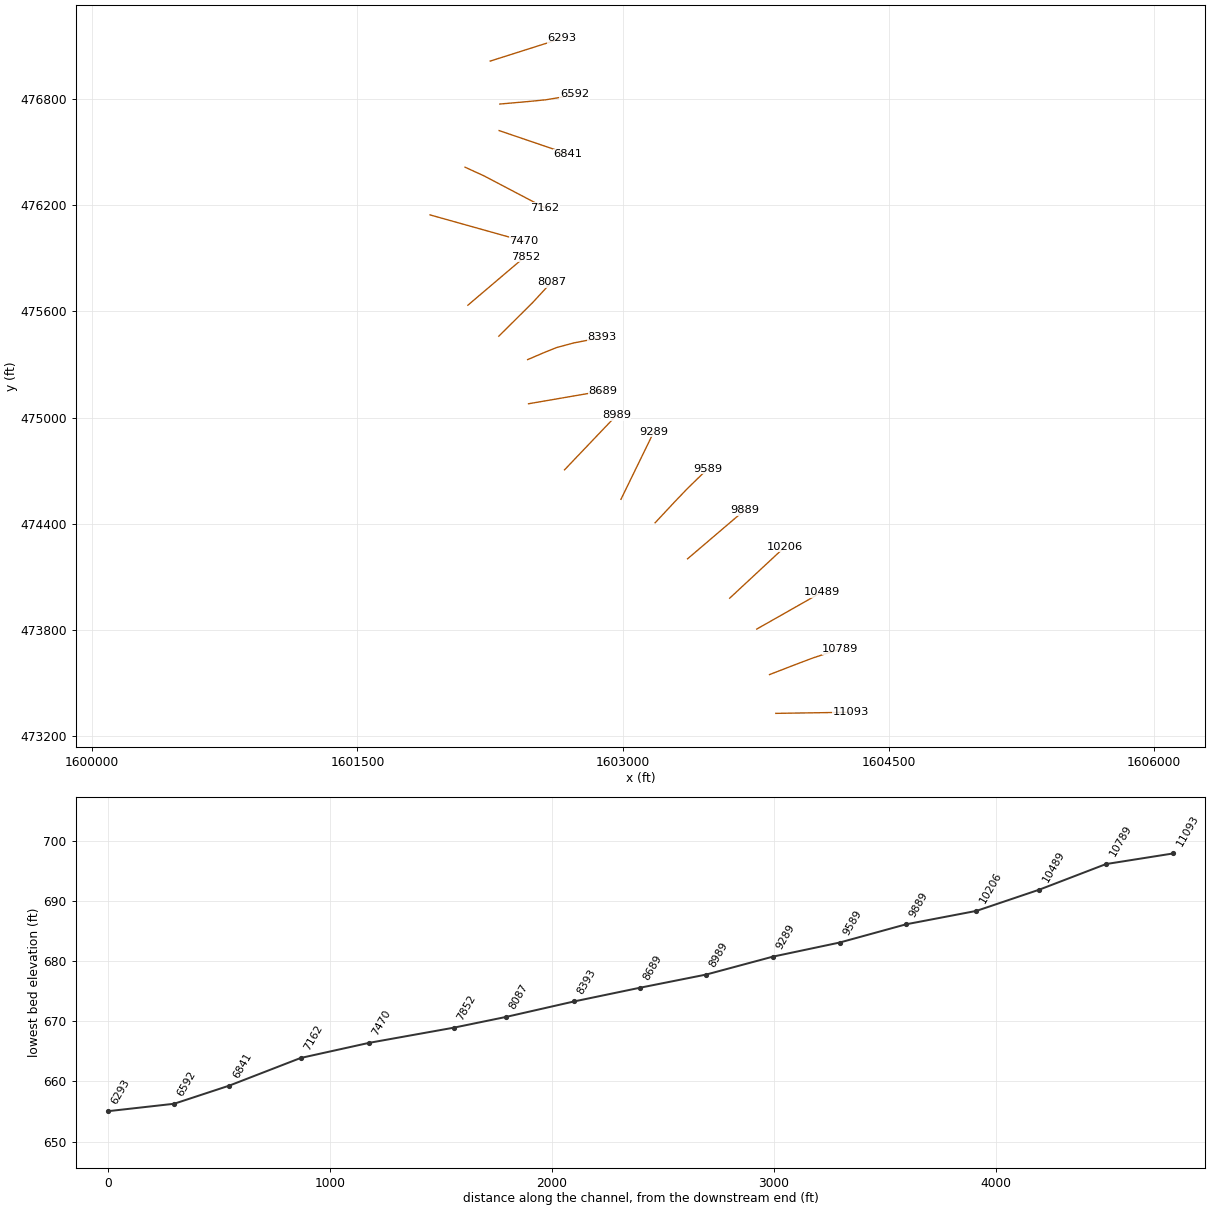
HEC-RAS study LngRn.prj: LngRn

--- LngRn.g01 (geometry) --- (continued)

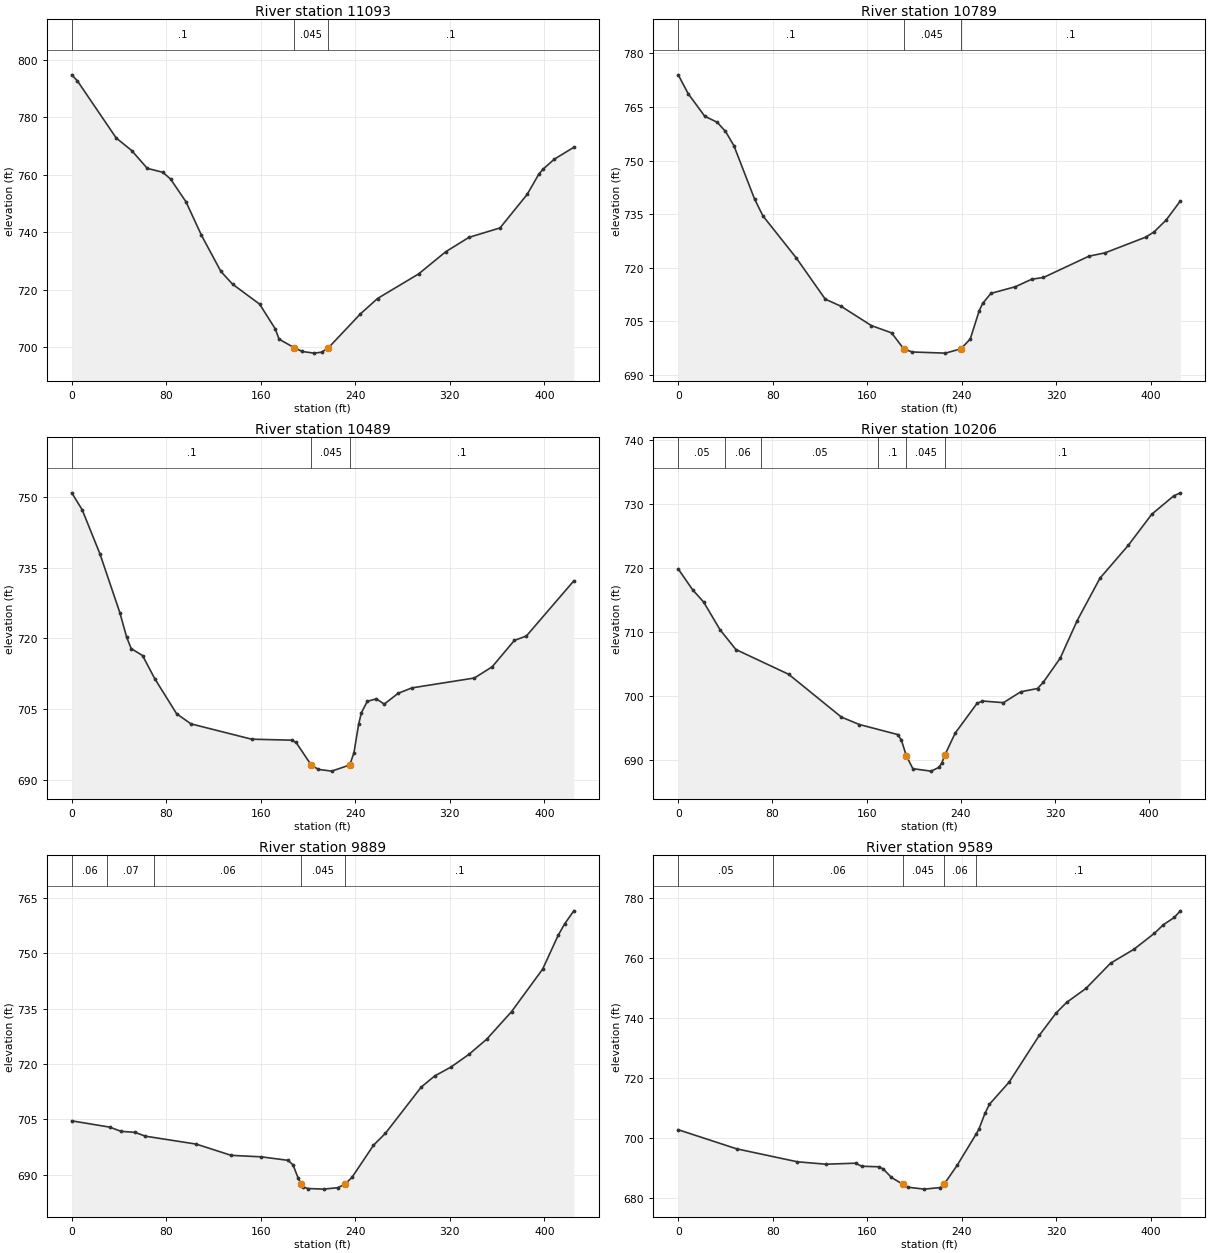
Type RM Length L Ch R = 1 ,11093   ,295.7,303.9,311
XS GIS Cut Line= 6
1603863.07757501473328.0562663381603950.57740001473329.432575926
 1604025.5775781473330.5726655131604125.56687942473332.043135002
1604200.54835676473333.2524501681604288.02620018473334.664520845
#Sta/Elev= 30
       0  794.84     4.8  792.71    37.6  772.84    50.8  768.43    63.9  762.25
      77  760.88    83.6  758.55    96.7  750.58   109.8  738.92   126.2  726.35
   136.1  721.89     159  714.94   172.2  706.35   175.5  702.72   188.5699.7054
   195.1  698.44     205  697.86   211.5  698.19   217.2699.7054   244.4  711.56
   258.8  716.89   293.6  725.46   316.5  733.18   336.2   738.2   362.5  741.49
   385.5  753.18   395.3   760.2   398.8  761.92   408.4  765.43     425  769.59
#Mann= 3 ,-1,0
       0      .1       0   188.5    .045       0   217.2      .1       0
Bank Sta=188.5,217.2
XS Rating Curve= 0 ,0
Exp/Cntr(USF)=0,0
Exp/Cntr=0.3,0.1

Type RM Length L Ch R = 1 ,10789   ,300.1,300.4,303.3
XS GIS Cut Line= 6
1603827.30369642473547.2375864981603908.90327075473578.824465588
1603978.84604426473605.8985584231604072.40359992473641.221322417
1604143.69381167473664.8141230051604227.16477334473691.567022249
#Sta/Elev= 30
       0  774.02     8.4  768.75    22.4  762.45      33  760.73      40  758.19
    47.1  754.22    64.6  739.27    71.7  734.53    99.9  722.78   124.5  711.21
   137.9  709.21   163.6   703.8   180.7  701.76     191697.2636   198.2  696.41
   226.3  696.09   239.2697.2748   247.3  700.02   254.9  707.99   257.8  710.01
   264.8  712.82   285.5  714.68   299.4  716.79   309.3  717.27   347.7  723.22
   361.5  724.18     396  728.58   403.1  730.07   413.2  733.36   425.2  738.68
#Mann= 3 ,-1,0
       0      .1       0     191    .045       0   239.2      .1       0
Bank Sta=191,239.2
XS Rating Curve= 0 ,0
Exp/Cntr(USF)=0,0
Exp/Cntr=0.3,0.1

Type RM Length L Ch R = 1 ,10489   ,280.2,282.7,287.7
XS GIS Cut Line= 6
1603755.26611084 473804.53103517 1603831.3633996473847.721893668
1603896.58964708473884.7424889211603983.55863325473934.102626428
1604048.78488076473971.1232216661604124.88249759474014.313424006
#Sta/Elev= 30
       0   750.9     8.8  747.31    23.9  737.91    40.7  725.47    46.5  720.23
    50.3  717.85    59.9  716.37    70.3  711.44    88.8     704   100.9  701.87
   152.2  698.62   186.1  698.41   189.9  697.92   202.7  693.13   208.7  692.21
   220.1  691.84   235.3 693.152   238.9  695.77   242.8  701.76   245.2  704.27
   250.2  706.66   257.8  707.18   264.5  706.06   276.3  708.36     288  709.51
   340.8   711.6   355.9  713.99   374.7  719.59   384.8  720.51     425  732.23
#Mann= 3 ,-1,0
       0      .1       0   202.7    .045       0   235.3      .1       0
Bank Sta=202.7,235.3
XS Rating Curve= 0 ,0
Exp/Cntr(USF)=0,0
Exp/Cntr=0.3,0.1

Type RM Length L Ch R = 1 ,10206   ,317.9,317.3,316
XS GIS Cut Line= 2
1603602.36877884473979.0769459161603914.60543716 474269.59484557
#Sta/Elev= 30
       0  719.86    12.3   716.6    21.6   714.7    35.5  710.38      49  707.29
    93.8  703.43   138.6  696.75   153.9  695.59   186.4  694.03   189.6  693.14
   193.8690.6933   199.3   688.7   214.8  688.32   221.3  688.89   223.8  689.54
   226.4690.7927   235.2  694.23   253.8  698.89   258.4  699.26   276.3     699
     291   700.7   305.2  701.21     310  702.16   324.5  705.95   338.9  711.81
   358.2  718.41   382.3  723.55   402.3  728.41   420.8  731.25   426.5  731.74
#Mann= 6 ,-1,0
       0     .05       0      40     .06       0      70     .05       0
     170      .1       0   193.8    .045       0   226.4      .1       0
Bank Sta=193.8,226.4
XS Rating Curve= 0 ,0
Exp/Cntr(USF)=0,0
Exp/Cntr=0.3,0.1

Type RM Length L Ch R = 1 ,9889    ,296.8,299.4,300.5
XS GIS Cut Line= 6
1603364.49589501474201.7018287631603431.06925267474258.484195501
1603488.13180259474307.1550299231603564.21498376474372.049913257
1603621.27786176474420.7207476791603687.85089134474477.503442511
#Sta/Elev= 30
       0  704.58    32.1  702.88    41.8  701.73    53.4  701.47    62.3  700.43
   105.4  698.28   134.9  695.24   160.5  694.83     183  693.89   187.3  692.66
   191.6   689.1   194.4687.3544   195.9  686.71   199.8  686.26   213.2  686.09
   225.1  686.48   231.2687.3835   237.3  689.32   255.4  697.97   265.5   701.2
   295.8  713.72   307.1  716.71   321.1  719.17   336.3  722.61   351.3  726.71
   372.3  734.17   398.6  745.67   411.8  754.86   417.2  757.92     425  761.45
#Mann= 5 ,-1,0
       0     .06       0      30     .07       0      70     .06       0
   194.4    .045       0   231.2      .1       0
Bank Sta=194.4,231.2
XS Rating Curve= 0 ,0
Exp/Cntr(USF)=0,0
Exp/Cntr=0.3,0.1

Type RM Length L Ch R = 1 ,9589    ,293.6,300.6,304.5
XS GIS Cut Line= 6
1603181.22592033474405.2742562591603240.92855684474469.241976082
1603292.10233901474524.0712627621603361.24491726474596.326695666
1603414.90983617474648.830855757  1603477.893306474709.736245751
#Sta/Elev= 30
       0  702.83    49.5  696.47   100.8  692.17   124.8  691.36   150.2  691.69
   155.3  690.68   169.7   690.5   173.6  689.78   180.5  686.97   190.3684.6382
   194.4   683.7   208.4  683.06   221.9  683.58     225 684.614   236.3  691.04
   252.5  701.53   254.8  703.19   259.8  708.34   263.6  711.33   280.3  718.72
   305.8  734.27   319.9  741.64     329  745.24   345.3  749.86   366.1  758.26
   385.9  762.89   403.3  768.23   410.9  771.08   420.1  773.49   425.2   775.7
#Mann= 5 ,-1,0
       0     .05       0      80     .06       0   190.3    .045       0
     225     .06       0   252.5      .1       0
Bank Sta=190.3,225
XS Rating Curve= 0 ,0
Exp/Cntr(USF)=0,0
Exp/Cntr=0.3,0.1

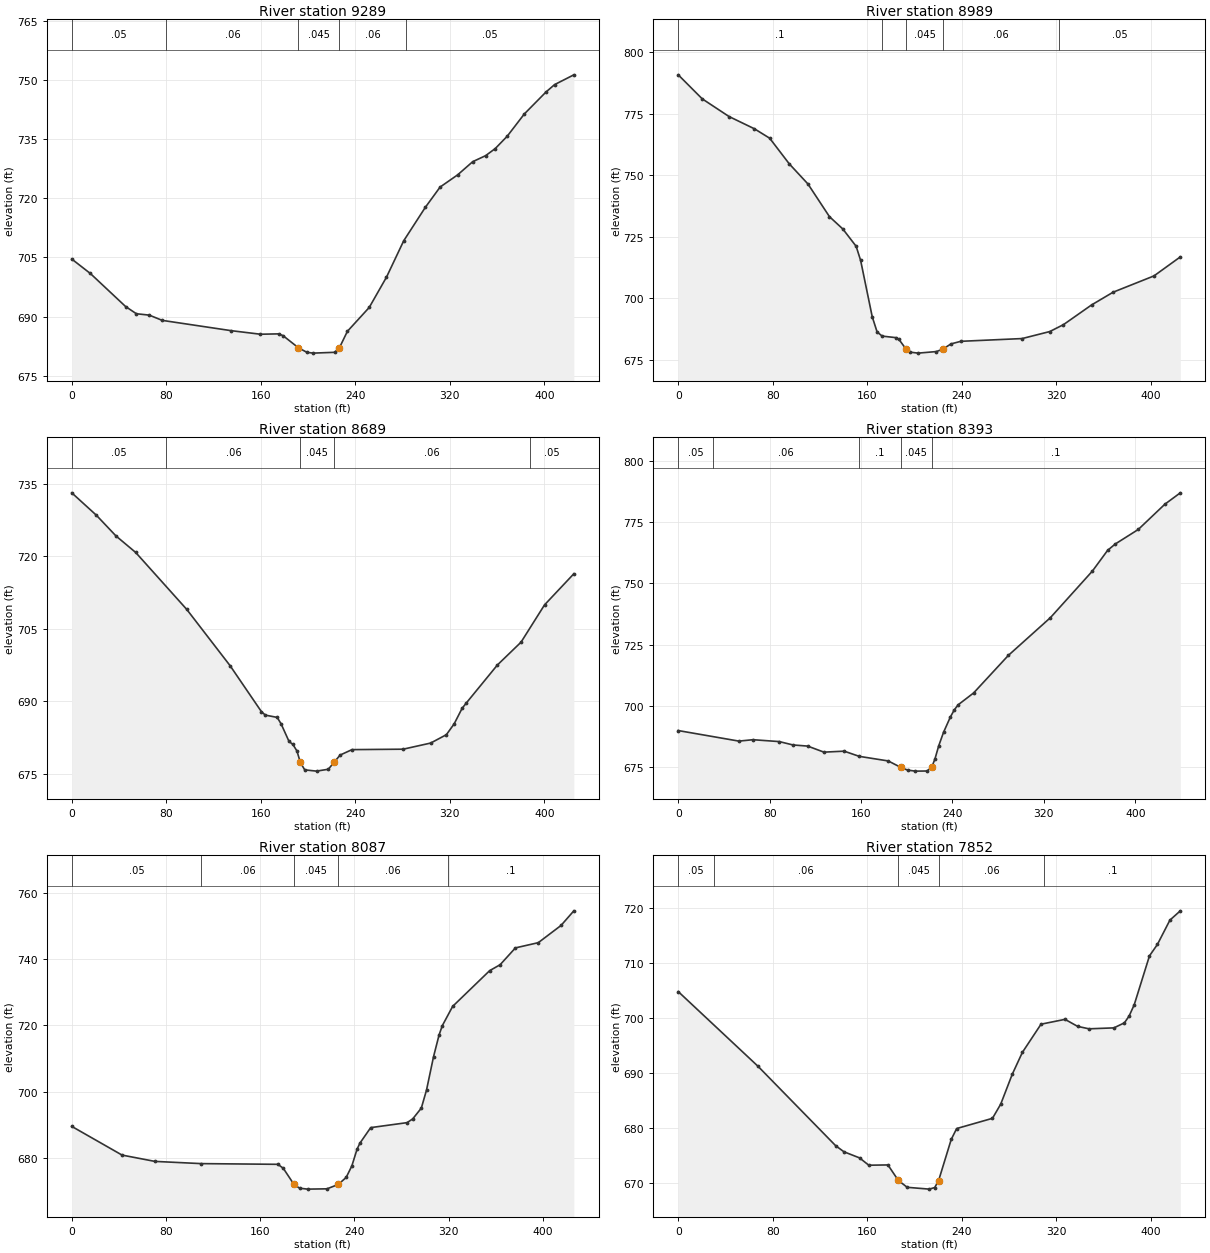
Type RM Length L Ch R = 1 ,9289    ,305.5,300,296.2
XS GIS Cut Line= 6
1602988.35327458474538.0768121781603026.67603259474616.738400251
  1603059.524064   474684.162478 1603103.3212205474774.061248332
1603136.16925192474841.4853260821603174.49200992 474920.14658609
#Sta/Elev= 30
       0  704.56    15.7  700.91    45.6  692.52    54.7   690.7    65.6  690.35
    76.6  689.02     135  686.41   159.7  685.51   175.1   685.6   178.8  685.16
   191.9682.0634     199  680.93   204.3  680.72   222.6  680.93   226.5682.0409
   233.3  686.24   251.8   692.3   266.4  699.97     281   709.2   299.2  717.63
   311.8  722.81   326.6  725.89   339.4  729.24   350.3  730.76   358.5  732.57
   368.6  735.69   383.1  741.34   401.4  746.89   408.7  748.77     425  751.25
#Mann= 5 ,-1,0
       0     .05       0      80     .06       0   191.9    .045       0
   226.5     .06       0   282.5     .05       0
Bank Sta=191.9,226.5
XS Rating Curve= 0 ,0
Exp/Cntr(USF)=0,0
Exp/Cntr=0.3,0.1

Type RM Length L Ch R = 1 ,8989    ,312.1,300,293.1
XS GIS Cut Line= 6
1602669.54551326474704.5318598451602729.85805668474767.937244833
1602781.58203459474822.2475036681602850.54744785 474894.66140084
1602902.27142575474948.9719877541602962.57117392475012.364577502
#Sta/Elev= 30
       0  790.86    20.3   781.1      43  773.91    64.5  768.93    77.4   765.1
      94  754.67   109.8   746.5     128  733.22   139.3  728.22   150.6  721.17
   154.4  715.42   164.2  692.56   168.3   686.4   172.6  684.67   184.5  684.03
   186.8  683.34   192.8679.4169   196.1  678.16   203.1  677.75   218.6  678.39
   224.1679.4144   230.9   681.5   239.2  682.55   291.1  683.67   314.5  686.52
   326.1  689.33   349.9  697.34   368.1  702.51   402.7  709.13     425  716.86
#Mann= 5 ,-1,0
       0      .1       0  172.51     .06       0   192.8    .045       0
   224.1     .06       0  322.51     .05       0
Bank Sta=192.8,224.1
XS Rating Curve= 0 ,0
Exp/Cntr(USF)=0,0
Exp/Cntr=0.3,0.1

Type RM Length L Ch R = 1 ,8689    ,294.1,295.9,296.5
XS GIS Cut Line= 6
1602466.21882017475077.9946955891602552.44666609475092.861463755
1602626.35629517 475105.604220421602724.90202984475122.594672009
1602798.81165892475135.3374286741602885.13825792475149.632019505
#Sta/Elev= 30
       0  733.15    20.8  728.52    37.4  724.23    54.1  720.81    97.3  709.03
     134  697.38   160.6  687.84   163.9  687.14   173.9  686.67   177.2  685.33
   183.9   681.7   187.2  681.07   190.6  679.72   193.5 677.348   197.2  675.81
   207.2  675.55   217.2  675.94   221.9677.3441   227.2  678.88   237.2     680
   280.5  680.09   303.8  681.36   317.1  683.09   323.7  685.34   330.4  688.54
   334.1  689.69   360.3  697.52   380.3  702.24   400.2  709.96     425   716.4
#Mann= 5 ,-1,0
       0     .05       0      80     .06       0   193.5    .045       0
   221.9     .06       0   387.5     .05       0
Bank Sta=193.5,221.9
XS Rating Curve= 0 ,0
Exp/Cntr(USF)=0,0
Exp/Cntr=0.3,0.1

Type RM Length L Ch R = 1 ,8393    ,294.3,306.3,309.1
XS GIS Cut Line= 6
  1602461.143371475327.4577793331602551.09365043475366.055143088
1602624.17290059475395.4920920881602720.96699834475421.632131666
1602794.59644426475435.9053970871602880.49719109475452.557594761
#Sta/Elev= 30
       0  689.86    53.1  685.55    65.4  686.12    88.5  685.35   100.4  683.98
   113.3  683.51   127.5  681.04   145.2  681.44   158.4  679.32   183.8  677.44
   194.8674.8011   200.8  673.69   207.6  673.28   217.8  673.33   221.8 674.876
   224.6  678.15     228  683.67   232.2  689.16   238.2  695.44   241.6  698.32
     245   700.4   258.5  705.23   288.9  720.58   325.7     736   362.5  755.07
   375.8  763.53   382.5  766.12   402.6  772.05   425.9  782.38   439.4  787.03
#Mann= 5 ,-1,0
       0     .05       0      30     .06       0  157.88      .1       0
   194.8    .045       0   221.8      .1       0
Bank Sta=194.8,221.8
XS Rating Curve= 0 ,0
Exp/Cntr(USF)=0,0
Exp/Cntr=0.3,0.1

Type RM Length L Ch R = 1 ,8087    ,234.7,235,232.5
XS GIS Cut Line= 3
1602298.31954968475459.9312676791602489.25599537475649.580794839
1602595.79303609475765.199029833
#Sta/Elev= 30
       0   689.6    42.7  680.96    70.6  679.06     110  678.39     175  678.18
   179.6  676.98   188.7 672.105   193.5  670.99   200.2  670.71   216.7   670.8
   226.3672.1243     233  674.24   237.8  677.69   242.2   682.7   244.6  684.52
   253.8  689.23   284.7  690.73   289.5  691.86   296.8  695.11   301.2  700.53
   307.2  710.64   311.9  717.17   314.6  719.92   323.4  725.74   354.8  736.49
   363.7  738.28   376.7  743.35   396.1  744.92   415.4   750.1   426.3  754.51
#Mann= 5 ,-1,0
       0     .05       0     110     .06       0   188.7    .045       0
   226.3     .06       0  319.12      .1       0
Bank Sta=188.7,226.3
XS Rating Curve= 0 ,0
Exp/Cntr(USF)=0,0
Exp/Cntr=0.3,0.1

Type RM Length L Ch R = 1 ,7852    ,394.1,381.4,361.2
XS GIS Cut Line= 2
1602123.66474318475635.0422468191602447.48758635475910.294320986
#Sta/Elev= 30
       0  704.86    67.4   691.3   133.3  676.82   140.3  675.72   153.5  674.61
   161.3  673.28   177.5  673.33   186.3670.5175   193.8  669.26   212.5  668.93
   217.1  669.22   220.4  670.49   231.1  677.98   235.7  679.95     266  681.81
     273   684.4   282.7   689.8   291.3   693.8   307.1  698.93   327.4  699.81
   338.1  698.53   347.7  698.09   368.8  698.26   377.7  699.18   381.7  700.43
     386  702.47   398.9  711.36   405.6  713.43   416.2  717.86     425  719.55
#Mann= 5 ,-1,0
       0     .05       0      30     .06       0   186.3    .045       0
   220.4     .06       0     310      .1       0
Bank Sta=186.3,220.4
XS Rating Curve= 0 ,0
Exp/Cntr(USF)=0,0
Exp/Cntr=0.3,0.1

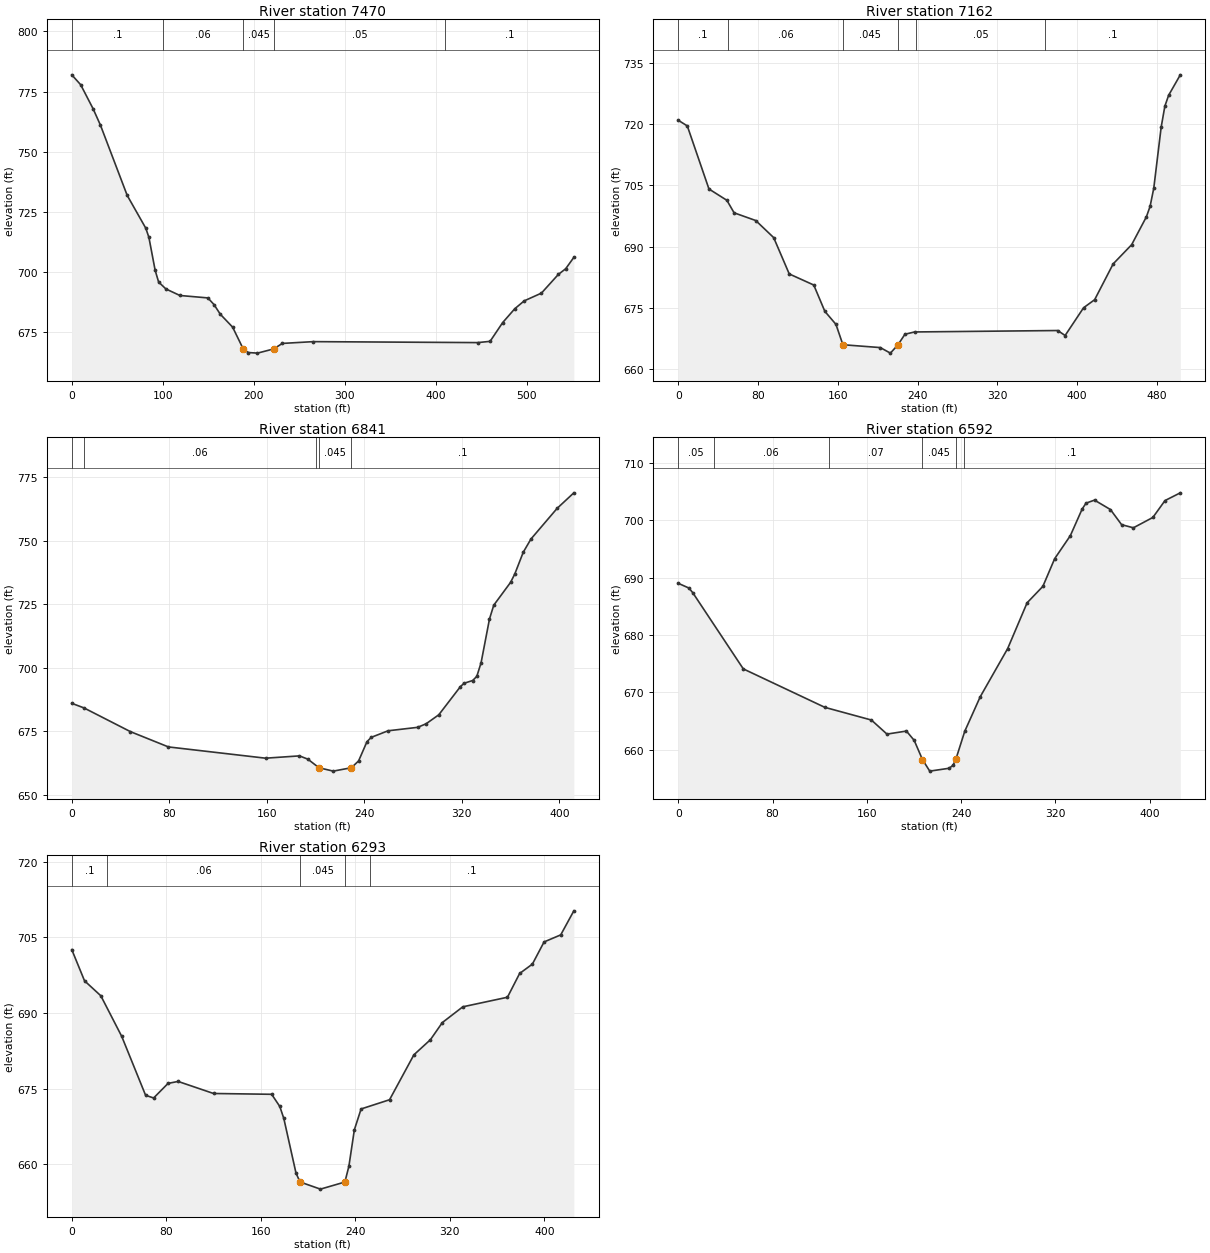
Type RM Length L Ch R = 1 ,7470    ,308.3,308.1,304.9
XS GIS Cut Line= 2
 1601909.6882148476145.5380241611602440.75446573475996.704498862
#Sta/Elev= 30
       0  781.94     9.8  777.82    23.4  767.87    31.5  761.05    60.9  731.87
    81.3  718.27    84.7   714.5    91.6  700.77    95.4  695.93   103.4  693.05
   118.8  690.34   149.5  689.33   156.3  686.54   163.1  682.58   176.7  677.19
   188.3  668.17   193.8  666.66     204  666.41   221.8668.1577   231.3  670.44
   265.3  671.18   445.9  670.78   459.5   671.3   473.3  679.08   486.6  684.83
     497  688.11   515.9  691.32   534.5  699.09   542.5  701.42   551.5  706.16
#Mann= 5 ,-1,0
       0      .1       0     100     .06       0   188.3    .045       0
   221.8     .05       0     410      .1       0
Bank Sta=188.3,221.8
XS Rating Curve= 0 ,0
Exp/Cntr(USF)=0,0
Exp/Cntr=0.3,0.1

Type RM Length L Ch R = 1 ,7162    ,322.7,320.8,317.4
XS GIS Cut Line= 3
1602107.67449635476415.056424781 1602215.0197441476365.937552804
1602556.15421994476186.689420829
#Sta/Elev= 30
       0  720.98     9.1  719.58    30.8  704.13    48.8  701.35      56  698.29
    77.7   696.4    95.7  692.21   111.3  683.31   135.9  680.59     147  674.14
   158.1  670.96   165.1665.9586   202.6  665.26   212.7   663.9   220.3665.9355
   227.3  668.53     237  669.09   380.5  669.44   387.9  668.22   406.4  675.02
   417.5  676.99   436.1  685.78   454.6  690.47   469.4  697.31   473.1  699.87
   476.8  704.34   484.2  719.27   487.9  724.42   491.7   727.1   503.4  732.11
#Mann= 6 ,-1,0
       0      .1       0      50     .06       0   165.1    .045       0
   220.3     .06       0  238.05     .05       0  368.05      .1       0
Bank Sta=165.1,220.3
XS Rating Curve= 0 ,0
Exp/Cntr(USF)=0,0
Exp/Cntr=0.3,0.1

Type RM Length L Ch R = 1 ,6841    ,244.6,249,255.6
XS GIS Cut Line= 2
1602300.06495301476622.0178542581602689.97905941476489.219861792
#Sta/Elev= 30
       0     686      10  684.19    48.1  674.86    79.3  668.84     159  664.41
   186.8  665.32   193.7  664.02   202.8660.6522   214.5  659.32   229.4660.6605
   235.3  663.33   242.2  670.91   245.7  672.61   259.5  675.19   283.8  676.55
   290.7  677.95   301.1  681.48   318.9   692.6   321.9  693.89   328.9  694.97
   332.3   696.6   335.8  701.95   342.7  719.19   346.2   724.6     360  733.58
   363.5  736.93   370.4  745.44   376.7  750.62   398.2   762.7   411.9   768.8
#Mann= 5 ,-1,0
       0      .1       0      10     .06       0     200      .1       0
   202.8    .045       0   229.4      .1       0
Bank Sta=202.8,229.4
XS Rating Curve= 0 ,0
Exp/Cntr(USF)=0,0
Exp/Cntr=0.3,0.1

Type RM Length L Ch R = 1 ,6592    ,296.2,299.4,301.8
XS GIS Cut Line= 6
1602303.71914518476771.9854020921602390.88038817476779.676659673
1602465.59021251476786.2688380931602565.10051218476796.221574083
1602639.30410393476808.5493053351602725.79277609476826.116199344
#Sta/Elev= 30
       0  689.02     9.1  688.19    12.4  687.36    55.2  674.11   124.4  667.41
   163.9   665.2   177.1  662.75   193.6  663.28   200.2  661.66   207.2658.3209
   213.4   656.3   229.9   656.8   233.2  657.33   235.5658.3267   243.1  663.24
   256.2  669.24   279.5  677.64     296  685.62   309.4  688.49   319.4  693.31
   332.7  697.32   342.7  701.95     346  702.98   353.2  703.51   366.7  701.87
   376.2  699.23   386.2  698.69   402.7  700.49     413  703.43     426  704.78
#Mann= 6 ,-1,0
       0     .05       0      30     .06       0   127.5     .07       0
   207.2    .045       0   235.5     .07       0   242.5      .1       0
Bank Sta=207.2,235.5
XS Rating Curve= 0 ,0
Exp/Cntr(USF)=0,0
Exp/Cntr=0.3,0.1

Type RM Length L Ch R = 1 ,6293    ,298,300,300.9
XS GIS Cut Line= 6
1602249.97942325477014.8769766691602333.41068684477041.301136419
1602404.89315543477064.0002380011602500.20300417477094.266581669
1602571.68514468477116.9660113451602655.08688076477143.380328596
#Sta/Elev= 30
       0  702.57    10.8  696.38    24.6  693.41    42.3  685.35    62.5  673.67
    69.3  673.14    81.5  676.03      90  676.42     120  674.03   169.2  673.87
   176.1  671.45   179.5  669.07   189.8  658.25   193.2656.4785   210.5  655.06
   231.2  656.47   234.6  659.62   239.2  666.82   244.9  670.96     269  672.79
   289.6   681.7   303.6   684.7   313.7   688.1     331  691.22   368.8  693.12
   379.1  697.83   389.9  699.69   399.8  704.09   413.9  705.49     425  710.26
#Mann= 5 ,-1,0
       0      .1       0      30     .06       0   193.2    .045       0
   231.2     .06       0  252.52      .1       0
Bank Sta=193.2,231.2
XS Rating Curve= 0 ,0
Exp/Cntr(USF)=0,0
Exp/Cntr=0.3,0.1