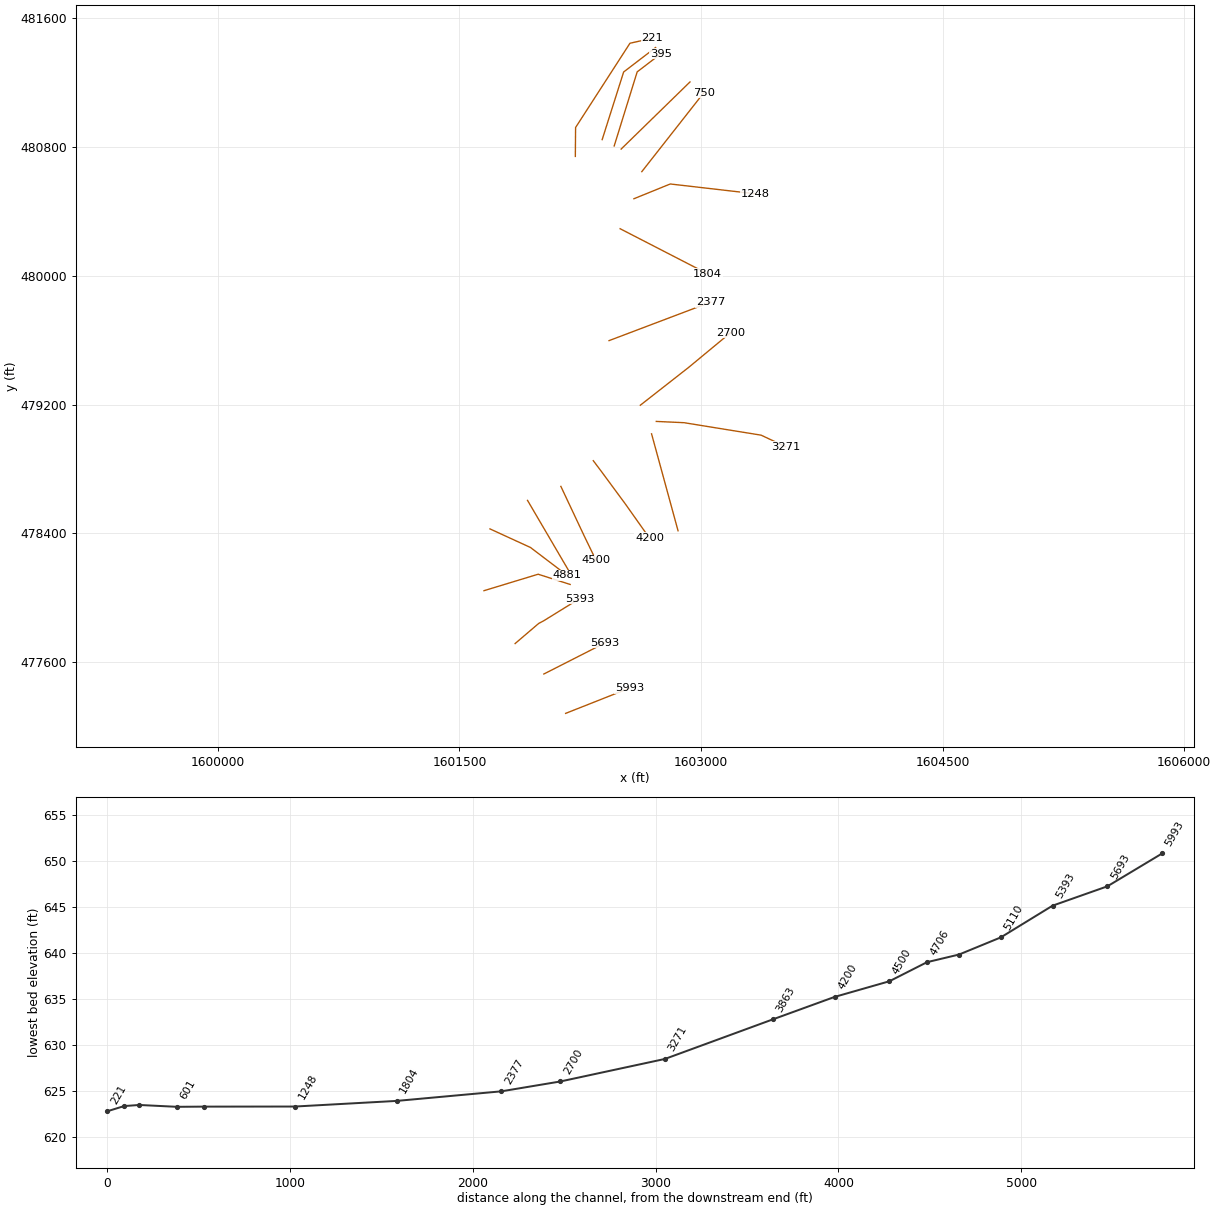
HEC-RAS study LngRn.prj: LngRn

--- LngRn.g01 (geometry) --- (continued)

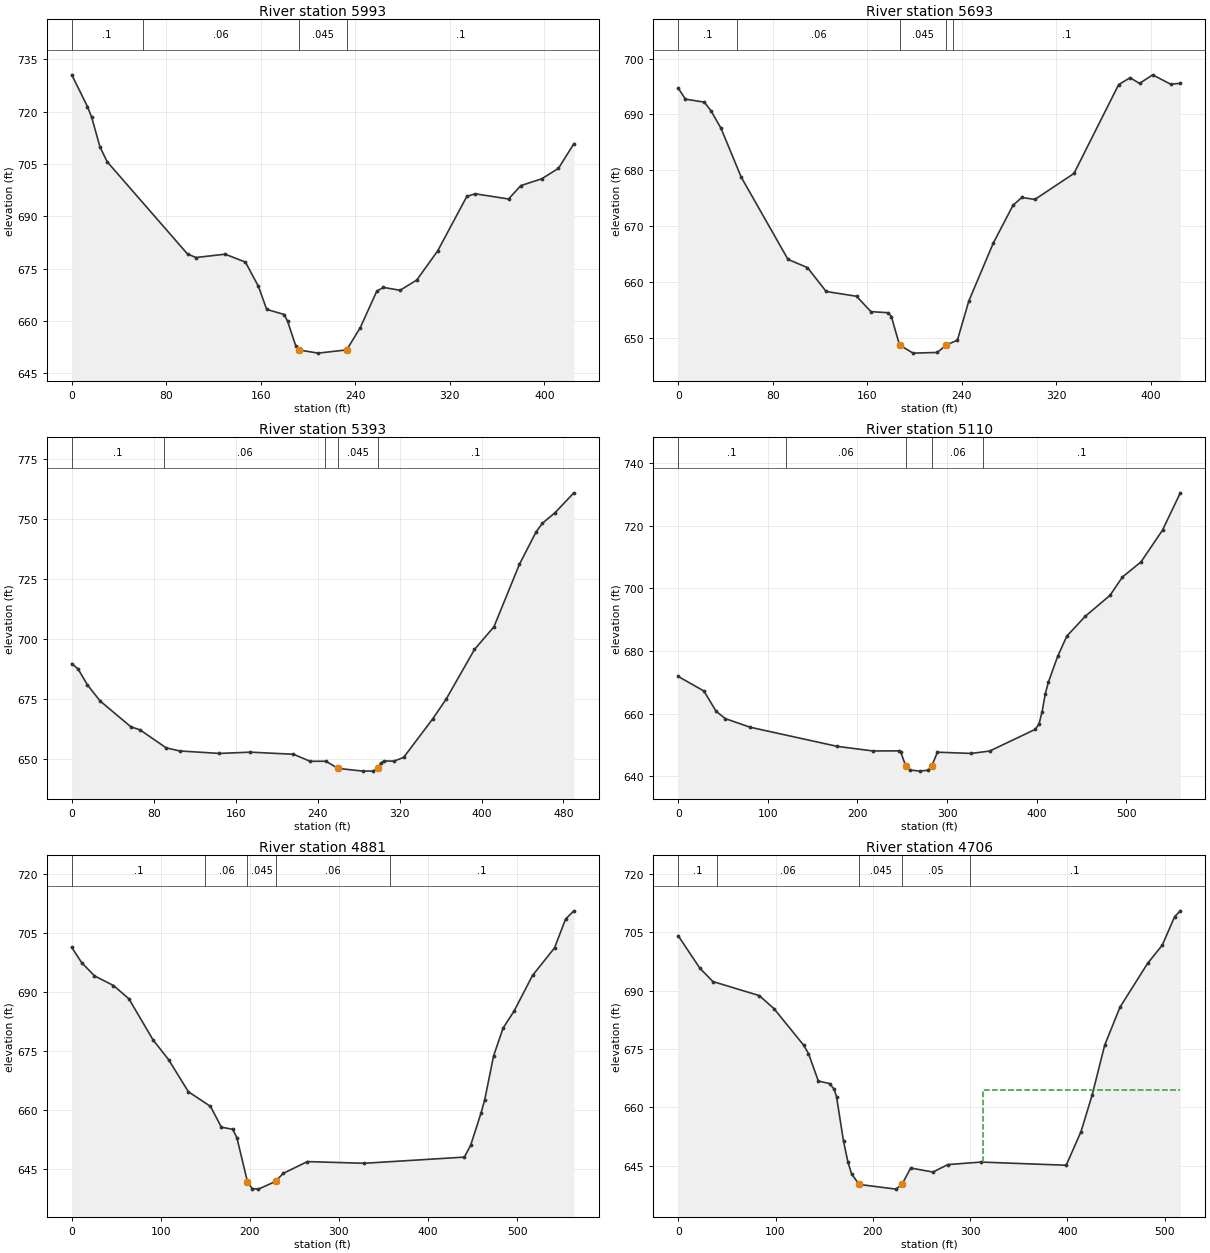
Type RM Length L Ch R = 1 ,5993    ,298.1,300,302.1
XS GIS Cut Line= 6
1602159.33327909 477282.883330421602240.70450743477315.053869754
1602310.45141518477342.6286177491602403.44729218477379.394948423
1602473.19419992477406.9693683391602554.56575634477439.139907673
#Sta/Elev= 30
       0  730.51    13.3   721.4    16.9  718.29    23.9  709.83      30  705.59
      98  679.17   105.1  678.17   129.8  679.13     147  676.86     158  669.91
     165  663.31   179.9  661.84   182.7   659.9   189.7  652.76   192.1651.7042
   208.5  650.78   232.7651.7067   244.2  658.08   258.2  668.54   263.8  669.61
   277.9  668.78     292  671.72   309.7  680.05   334.4  695.67   341.4  696.43
   369.7  694.94   380.2  698.79   397.9  700.73     412  703.73     425  710.77
#Mann= 4 ,-1,0
       0      .1       0      60     .06       0   192.1    .045       0
   232.7      .1       0
Bank Sta=192.1,232.7
XS Rating Curve= 0 ,0
Exp/Cntr(USF)=0,0
Exp/Cntr=0.3,0.1

Type RM Length L Ch R = 1 ,5693    ,298.2,300,301.4
XS GIS Cut Line= 6
1602024.08584617477527.3644687531602102.07322301477567.040898591
1602168.91954601477601.0493607521602258.04797667477646.394086346
1602324.89429967477680.4022204281602402.44959076 477720.92772992
#Sta/Elev= 30
       0  694.69     6.1  692.72    22.1  692.18    27.8  690.61    36.2   687.5
    53.3  678.75    92.9  664.01   109.4  662.54   125.2  658.26   150.9   657.4
   163.1  654.65   177.7  654.45   180.4  653.77   187.3648.6686   198.8  647.21
   219.2  647.33     227648.6783   236.3  649.53     246  656.57   266.6  666.89
   283.4  673.71   290.8   675.1   301.9  674.75     335  679.41   372.8  695.33
   382.5  696.56   390.5  695.54   401.6  697.08   416.8   695.4     425  695.56
#Mann= 5 ,-1,0
       0      .1       0      50     .06       0   187.3    .045       0
     227     .06       0   232.5      .1       0
Bank Sta=187.3,227
XS Rating Curve= 0 ,0
Exp/Cntr(USF)=0,0
Exp/Cntr=0.3,0.1

Type RM Length L Ch R = 1 ,5393    ,289.1,283.1,282.2
XS GIS Cut Line= 6
1601845.58554007477716.5484842981601991.90297473477841.384212494
1602023.00481158477857.9264716661602108.11553375477910.426038593
1602171.94841135 477949.800959841602246.41971909477995.738203928
#Sta/Elev= 30
       0  689.87     6.1  687.66    15.3  681.02    27.6  674.34    57.8  663.53
    66.5  662.33    92.1  654.81   105.3  653.51   144.1  652.48   174.3  653.01
   216.4  652.13   232.7   649.2   248.1  649.23     260 646.242   284.3  645.11
   294.4  645.17   298.5646.2426   302.1  648.65   304.9  649.34   314.4  649.26
   323.9  650.79   352.2  666.79   365.6  675.19   393.1  695.76   412.1   705.2
     437  731.24   453.1  744.58   459.3  748.26   471.7  752.68   490.1  760.97
#Mann= 5 ,-1,0
       0      .1       0      90     .06       0  247.56      .1       0
     260    .045       0   298.5      .1       0
Bank Sta=260,298.5
XS Rating Curve= 0 ,0
Exp/Cntr(USF)=0,0
Exp/Cntr=0.3,0.1

Type RM Length L Ch R = 1 ,5110    ,237.5,228.5,215.4
XS GIS Cut Line= 3
1601652.21833996478044.846716522 1601988.5543577478147.081012664
 1602187.3125395478083.626824735
#Sta/Elev= 30
       0  671.88    28.6  667.25    42.3  660.76    52.6  658.42    80.1  655.69
   177.4  649.57   217.2  648.11   245.8  648.13   248.4  647.66   253.8643.3292
   258.4  642.04   269.4  641.67     279  641.97   282.8643.2946   289.2  647.71
     327  647.32   347.5  648.08   398.2  654.98   402.6  656.72     406  660.69
   409.5  666.26   412.9  669.96   423.3  678.26   433.6  684.77   454.3  691.12
   481.8  697.77   495.6  703.61   516.3  708.42   540.4  718.61   560.2  730.48
#Mann= 5 ,-1,0
       0      .1       0     120     .06       0   253.8    .045       0
   282.8     .06       0     340      .1       0
Bank Sta=253.8,282.8
XS Rating Curve= 0 ,0
Exp/Cntr(USF)=0,0
Exp/Cntr=0.3,0.1

Type RM Length L Ch R = 1 ,4881    ,181.7,175.4,162.7
XS GIS Cut Line= 3
 1601689.2597516 478428.595741171601941.14135079478313.026536836
1602169.31644653478139.672730335
#Sta/Elev= 30
       0  701.35      11  697.49    25.5   694.1    46.8  691.64    64.1  688.27
    91.3  677.79   108.7  672.77   130.9  664.61   155.7  660.88     168  655.58
   180.7  655.04   185.4  652.88   197.2641.7423   202.4  639.96   209.6  639.81
   228.8641.7761   237.3  643.81   264.5  646.82   328.4  646.39   440.8  647.96
   447.9  651.01   459.6  659.25   463.7  662.62   473.6  673.75   484.3  680.82
   496.7  685.17   517.3   694.2     542  701.21   554.4  708.54   563.7  710.65
#Mann= 5 ,-1,0
       0      .1       0     150     .06       0   197.2    .045       0
   228.8     .06       0  357.13      .1       0
Bank Sta=197.2,228.8
XS Rating Curve= 0 ,0
Exp/Cntr(USF)=0,0
Exp/Cntr=0.3,0.1

Type RM Length L Ch R = 1 ,4706    ,207.8,205.9,203.9
XS GIS Cut Line= 2
1601922.47424735478605.7968241321602183.34661506478160.538297256
#Sta/Elev= 30
       0  704.12    22.3  695.76    35.6  692.36    83.2  688.75    98.4   685.4
   128.8  676.03   133.9  673.85     144  666.78   155.5  666.13   160.3  664.66
   162.7  662.76   169.9   651.3   174.4  645.98   178.2  642.89     186 640.185
   223.8  638.98   229.9640.1774     239  644.41   261.9  643.37   277.1  645.29
   311.3  645.94   398.8  645.12     414  653.77   425.4  663.11   438.4  676.03
   454.1  685.76   482.4     697   497.6  701.73   510.3  709.06   516.1  710.54
#Mann= 5 ,-1,0
       0      .1       0      40     .06       0     186    .045       0
   229.9     .05       0     300      .1       0
#XS Ineff= 2 , 0
                          313.21          664.36
Permanent Ineff=
       F       F
Bank Sta=186,229.9
XS Rating Curve= 0 ,0
Exp/Cntr(USF)=0,0
Exp/Cntr=0.3,0.1

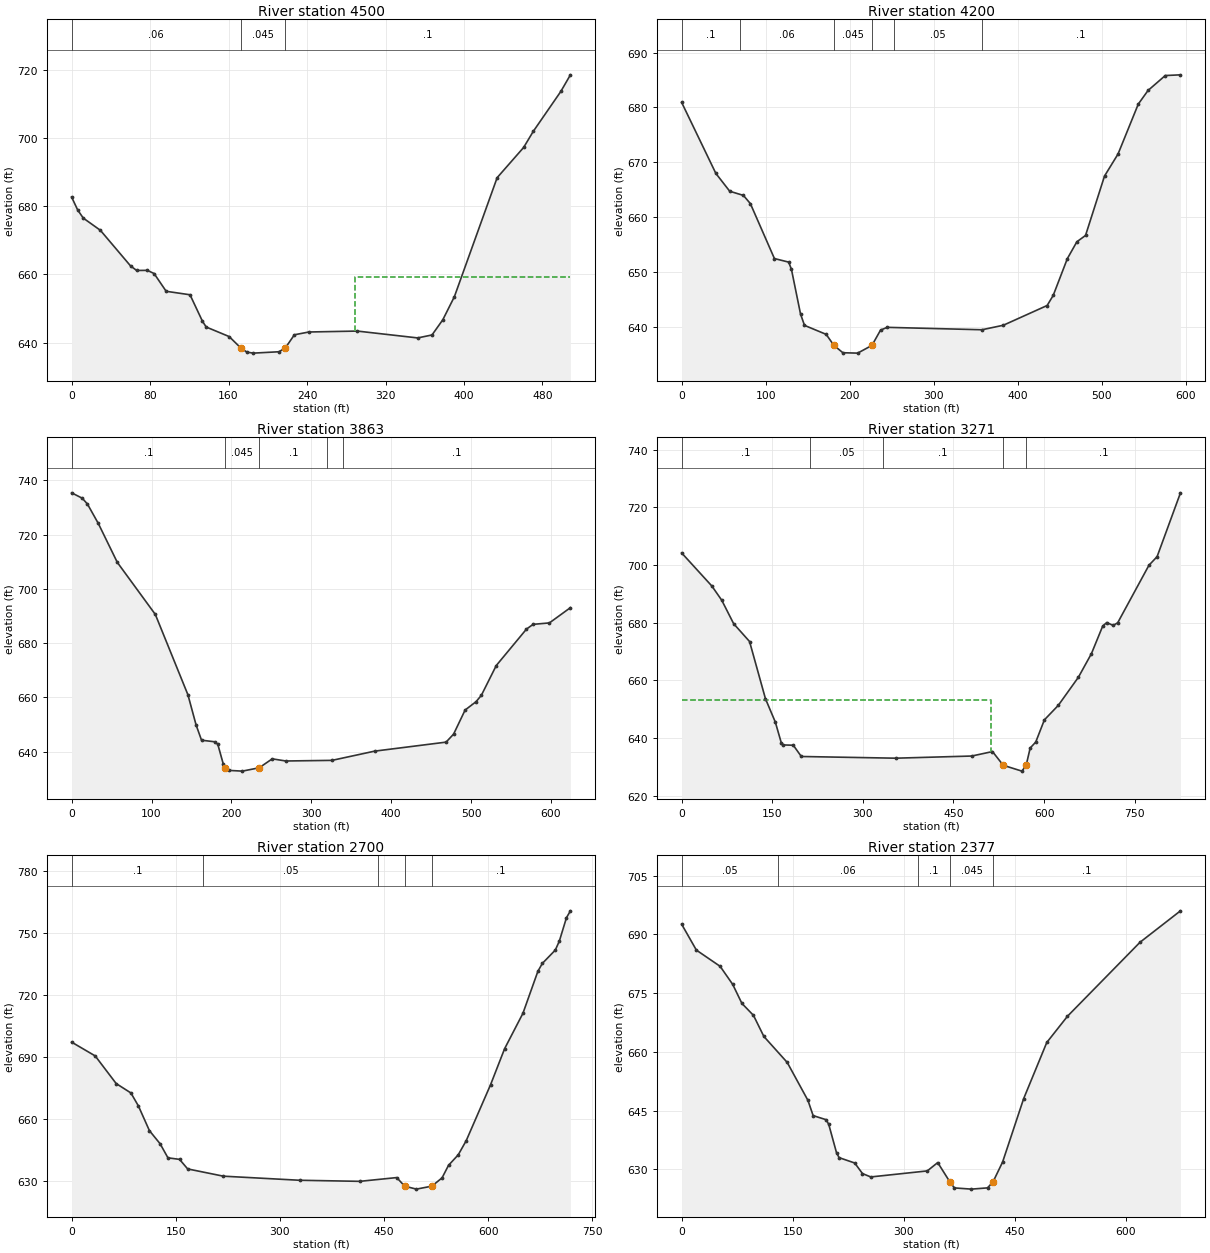
Type RM Length L Ch R = 1 ,4500    ,291.7,300,300.8
XS GIS Cut Line= 6
1602129.72375825478692.4782802611602166.98155776478613.307178751
1602198.91653326478545.4457659271602241.49682868478454.964319587
1602273.43213226478387.1032348421602348.02767469478233.256319376
#Sta/Elev= 30
       0   682.7     6.2   678.9    11.9  676.52    29.3  672.95    60.1  662.49
    66.3  661.16    77.2  661.19    84.1  660.26    96.4  655.05   120.7  654.03
   133.4  646.26   137.2  644.57   160.6  641.77   172.6638.3985   178.7   637.2
   185.2  636.91   211.3  637.31   217.8638.3943   227.1  642.29   241.9  643.11
   291.2  643.38   352.8  641.37   367.4  642.24   378.4  646.69   390.2  653.46
   433.8  688.38   460.8  697.24   470.6  701.95   498.7  713.67   508.5  718.55
#Mann= 3 ,-1,0
       0     .06       0   172.6    .045       0   217.8      .1       0
#XS Ineff= 2 , 0
                          289.39          659.37
Permanent Ineff=
       F       F
Bank Sta=172.6,217.8
XS Rating Curve= 0 ,0
Exp/Cntr(USF)=0,0
Exp/Cntr=0.3,0.1

Type RM Length L Ch R = 1 ,4200    ,346.1,337.1,330.8
XS GIS Cut Line= 6
1602331.06784375478852.0399690121602383.66091442478782.104413345
1602428.15065484478721.7252690051602487.47074617478641.219524503
1602531.96015851478580.8400520831602679.87624931478371.714562468
#Sta/Elev= 30
       0  680.91    40.7  667.97    57.2  664.72    73.5  663.96    81.8  662.46
   110.4  652.45   127.4   651.8   130.7  650.46   141.5  642.33   146.2  640.27
     172  638.63   181.2636.6255   191.9  635.28   209.5  635.21   226.5636.6218
   236.7   639.4   244.6  639.91   357.4  639.47   382.8  640.29     435  643.89
   442.2  645.72   459.1  652.45   470.4  655.51   480.7  656.66   503.3  667.49
   519.4  671.51   543.5  680.61   555.1  683.09   575.6  685.81   593.7  685.94
#Mann= 6 ,-1,0
       0      .1       0      70     .06       0   181.2    .045       0
   226.5      .1       0   252.5     .05       0   357.5      .1       0
Bank Sta=181.2,226.5
XS Rating Curve= 0 ,0
Exp/Cntr(USF)=0,0
Exp/Cntr=0.3,0.1

Type RM Length L Ch R = 1 ,3863    ,560.6,591.5,602.8
XS GIS Cut Line= 2
1602692.90767126479019.0288082511602857.39894253478416.835979976
#Sta/Elev= 30
       0  735.45    13.3  733.47    19.8  731.32    33.4  724.16    57.2  709.79
   104.8  690.58   145.6  660.93   155.8  649.81   162.6  644.19   179.6  643.59
     183  642.64   189.9  635.33   192.1 634.009   196.7  633.05   213.7  632.78
   234.8634.0191   251.1  637.31   268.1  636.52   325.9  636.75   379.2  640.15
   468.7  643.48   478.1  646.44   492.5  655.32   506.1  658.38   512.8  660.73
   531.5  671.74   569.3  685.18   577.6  686.93     598  687.46   624.3  693.09
#Mann= 5 ,-1,0
       0      .1       0   192.1    .045       0   234.8      .1       0
     320     .05       0     340      .1       0
Bank Sta=192.1,234.8
XS Rating Curve= 0 ,0
Exp/Cntr(USF)=0,0
Exp/Cntr=0.3,0.1

Type RM Length L Ch R = 1 ,3271    ,546,571.4,579.5
XS GIS Cut Line= 4
1602722.15276968479096.0312944781602894.99380352479088.115572064
1603373.40135789479010.6744210571603525.67853921478939.441190102
#Sta/Elev= 30
       0  704.21      50  692.72    66.4  687.78    86.1  679.64   112.4  673.47
   138.7  653.63   155.1  645.48     165  638.26   168.3  637.57   184.8  637.47
   198.1  633.56   354.3  632.97   480.3  633.72   514.6  635.27   532.4630.5075
   563.3  628.48   570.3  630.48     577  636.51   586.2  638.57   600.5  646.27
   623.5   651.3   656.8  661.06   678.4  669.26   697.1  678.85   703.8  680.05
   714.4  679.04   721.9  679.98   773.6  699.93   787.1  702.92   825.8  725.07
#Mann= 5 ,-1,0
       0      .1       0  213.02     .05       0  333.02      .1       0
   532.4    .045       0   570.3      .1       0
#XS Ineff= 2 , 0
          511.91  653.05
Permanent Ineff=
       F       F
Bank Sta=532.4,570.3
XS Rating Curve= 0 ,0
Exp/Cntr(USF)=0,0
Exp/Cntr=0.3,0.1

Type RM Length L Ch R = 1 ,2700    ,328.3,323,308.4
XS GIS Cut Line= 6
1602622.94163757479196.5537967821602923.04599051479431.442025423
1602980.82573059479479.2595150921603057.86527467479543.016277343
1603115.64468667479590.8334389181603183.05432875479646.620728925
#Sta/Elev= 30
       0   697.2      34  690.51    64.2  677.14    85.4   672.6    96.2  666.32
   112.1  654.35   127.5     648   138.8  641.18   155.5  640.45   167.2  635.82
   218.6  632.31   328.4  630.33   415.2  629.81   468.4  631.63   479.8627.4736
   496.7  626.04     519627.4766   533.7   631.5     543  637.57     557  642.65
   568.5  649.51   603.6  676.61   623.8  694.02   650.2  711.15   671.7  731.45
   678.1  735.27   696.8  741.74   702.6  746.05   712.9  757.41   718.6  760.74
#Mann= 5 ,-1,0
       0      .1       0     190     .05       0   441.1      .1       0
   479.8    .045       0     519      .1       0
Bank Sta=479.8,519
XS Rating Curve= 0 ,0
Exp/Cntr(USF)=0,0
Exp/Cntr=0.3,0.1

Type RM Length L Ch R = 1 ,2377    ,589.3,573,552.8
XS GIS Cut Line= 2
1602428.73297658479597.7395449071603059.26011703  479836.4508644
#Sta/Elev= 30
       0   692.6    19.9  685.99      52  681.85      69  677.24    81.4  672.39
    97.1  669.32   111.1  663.95   142.7  657.31   170.7  647.62   177.7  643.74
   195.3  642.69   198.8   641.5   209.3  634.27   212.8  633.01   233.9  631.64
   244.4  628.94   255.6  628.08     332  629.62   346.1  631.75   362.5  626.82
   368.6  625.28   391.7  624.97   413.4  625.29   420.9626.8367   433.8   631.9
   462.2  648.05   493.5  662.41   521.5  669.11   619.5  687.99   674.2  696.02
#Mann= 5 ,-1,0
       0     .05       0     130     .06       0     320      .1       0
   362.5    .045       0   420.9      .1       0
Bank Sta=362.5,420.9
XS Rating Curve= 0 ,0
Exp/Cntr(USF)=0,0
Exp/Cntr=0.3,0.1

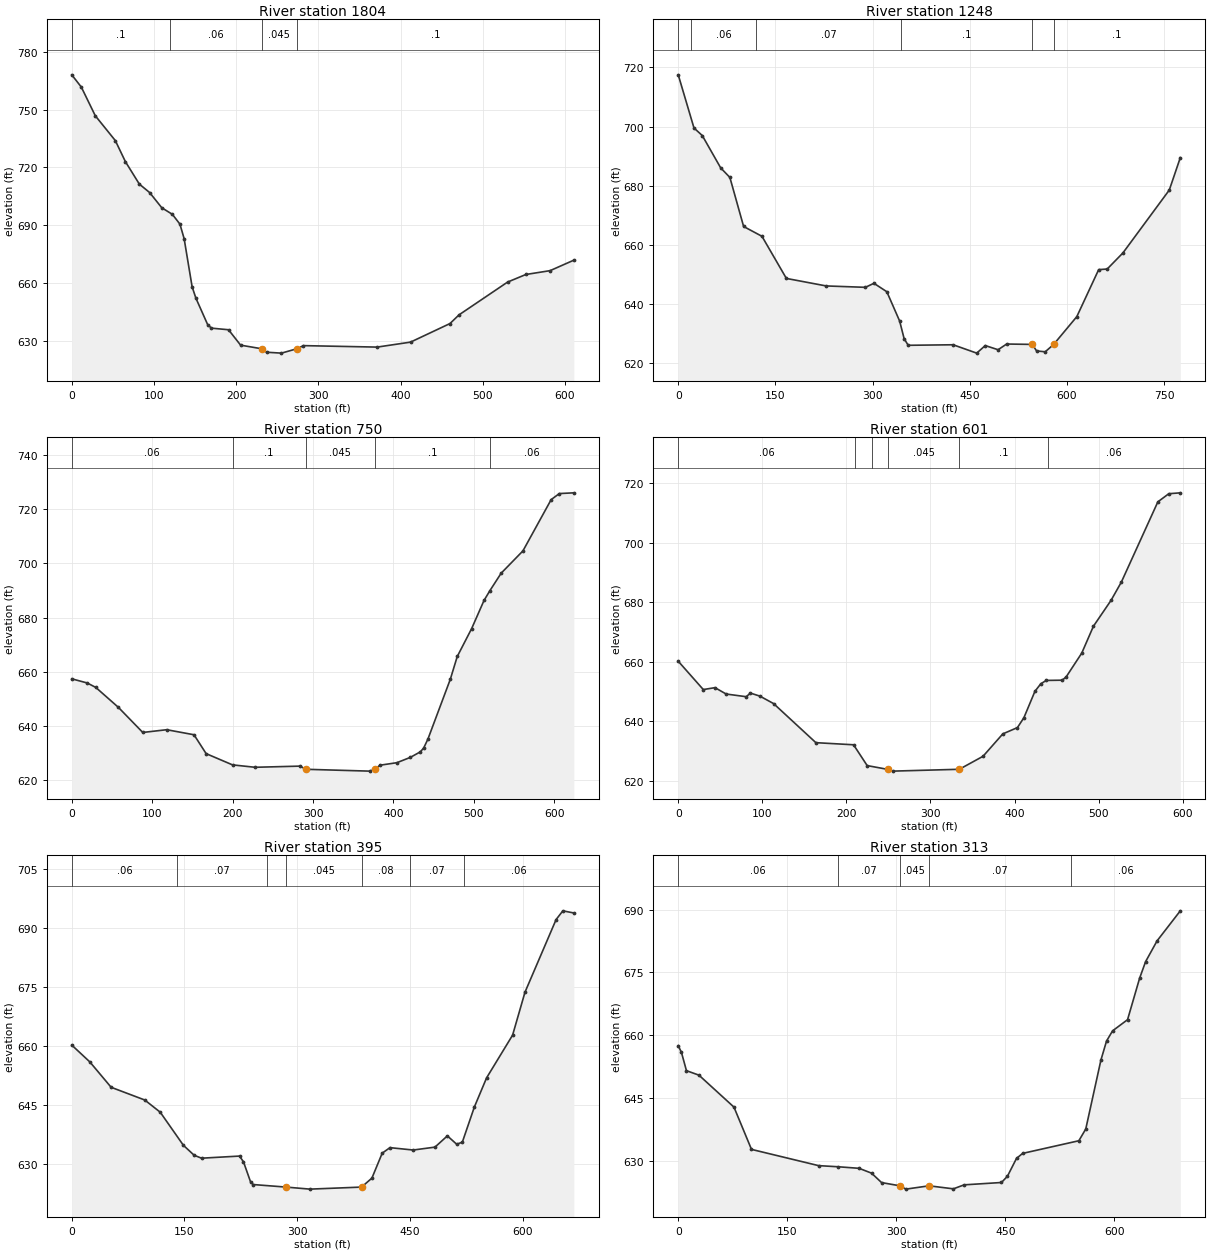
Type RM Length L Ch R = 1 ,1804    ,556.9,556.5,564.5
XS GIS Cut Line= 2
1602497.62326347 480292.828703341603040.57249717480013.108133042
#Sta/Elev= 30
       0  767.95    11.6  761.62    28.6  746.78      53  733.91    65.2  723.06
    82.2   711.4    94.7  707.04   109.5  699.16   122.4  695.75   131.6  690.67
   136.7  683.17   146.4  658.28     151  652.38   165.3   638.7   169.9  636.86
   190.7  636.03   205.4  628.06   231.4626.1627     237  624.39   255.1  623.93
   273.8626.1855   281.9  627.81   371.5  627.05   412.1  629.62   460.1  639.23
   471.2  643.76   530.2   660.7   552.4  664.62   581.9  666.61   610.8  672.04
#Mann= 4 ,-1,0
       0      .1       0     120     .06       0   231.4    .045       0
   273.8      .1       0
Bank Sta=231.4,273.8
XS Rating Curve= 0 ,0
Exp/Cntr(USF)=0,0
Exp/Cntr=0.3,0.1

Type RM Length L Ch R = 1 ,1248    ,480.4,497.7,521.9
XS GIS Cut Line= 3
 1602583.5081585480479.058960374 1602809.0248028480570.693957461
1603336.90055868 480509.79592564
#Sta/Elev= 30
       0  717.51    24.3  699.52    37.1  696.96    65.5  686.02    79.7  682.78
   100.9  666.18   129.2  662.86   166.9   648.6   228.3  646.06   288.8  645.59
     302  646.95   321.9   644.1   341.7  634.16   348.6  628.21   354.9  625.97
   424.2  626.15   460.6  623.32   473.8  625.88   493.6  624.47   506.8   626.4
   546.4  626.27     553  624.07   566.3  623.77  579.27  626.25   615.1  635.68
   648.8  651.57     662  651.79   686.2  657.22   757.8  678.52   774.8  689.49
#Mann= 6 ,-1,0
       0      .1       0      20     .06       0     120     .07       0
  343.42      .1       0   546.4    .045       0  579.27      .1       0
Bank Sta=546.4,579.27
XS Rating Curve= 0 ,0
Exp/Cntr(USF)=0,0
Exp/Cntr=0.3,0.1

Type RM Length L Ch R = 1 ,750     ,155.2,149.1,144.2
XS GIS Cut Line= 2
1602632.29244968480647.1653755441603017.91292007481138.221941118
#Sta/Elev= 30
       0  657.39    19.2  655.86    29.9  654.21      58  646.85    88.3  637.59
   118.1   638.6     152  636.74   167.1  629.77   199.9  625.62   227.9  624.73
     284  625.16     291  623.99   370.4  623.31   376.7623.9756   383.4   625.5
   404.3  626.42     421  628.38   433.6  630.45   437.7  631.88   442.9  635.12
   470.8  657.25   479.4  665.64   497.3  675.94   512.7  686.34     520  689.95
     534  696.39   561.1  704.64   596.2  723.57   606.4   725.8   624.4  726.07
#Mann= 5 ,-1,0
       0     .06       0     200      .1       0     291    .045       0
   376.7      .1       0     520     .06       0
Bank Sta=291,376.7
XS Rating Curve= 0 ,0
Exp/Cntr(USF)=0,0
Exp/Cntr=0.3,0.1

Type RM Length L Ch R = 1 ,601     ,180.9,205.2,228.6
XS GIS Cut Line= 2
1602504.01401431 480787.51461079 1602931.5224729481204.373392475
#Sta/Elev= 30
       0  660.21    29.8  650.69    43.7  651.33      57  649.19    80.9  648.29
    85.8  649.51    97.1  648.49   113.4  645.98   163.7  632.85   208.5  632.14
   224.7  625.15   249.7  623.85   254.9  623.29   334.3  623.91   362.5  628.28
     386   635.8   403.4  637.92   411.1  641.24   424.2   650.1   431.2  652.64
   437.7  653.76   456.7  653.84   461.4  654.97   479.9  662.94   493.8  671.98
   514.7  680.65     527   686.8   570.4  713.75   583.4  716.48   597.1  716.78
#Mann= 6 ,-1,0
       0     .06       0     210     .05       0     230      .1       0
   249.7    .045       0   334.3      .1       0     440     .06       0
Bank Sta=249.7,334.3
XS Rating Curve= 0 ,0
Exp/Cntr(USF)=0,0
Exp/Cntr=0.3,0.1

Type RM Length L Ch R = 1 ,395     ,88.1,82.9,85.2
XS GIS Cut Line= 3
1602460.82144998480806.7761949861602603.50496764481266.830527622
1602751.52244858481380.177247257
#Sta/Elev= 30
       0  660.22      24  655.94    52.4  649.46    97.1  646.22   117.7  643.11
   148.6  634.65   162.9  632.12   172.7  631.38   223.2  631.92   228.5  630.45
   237.9  625.35   241.4  624.66   285.5624.0044   316.9  623.49   385.6  624.01
   399.4   626.3   413.1  632.66   423.4  634.07   454.3  633.46   483.3   634.2
   499.8  637.07   512.2  634.94   519.7  635.46   535.8  644.47     552  651.87
   586.6  662.76   603.1  673.72   644.5  692.24   653.5  694.46   668.1  693.91
#Mann= 7 ,-1,0
       0     .06       0     140     .07       0     260     .08       0
   285.5    .045       0   385.6     .08       0     450     .07       0
  521.67     .06       0
Bank Sta=285.5,385.6
XS Rating Curve= 0 ,0
Exp/Cntr(USF)=0,0
Exp/Cntr=0.3,0.1

Type RM Length L Ch R = 1 ,313     ,100,91.2,103.7
XS GIS Cut Line= 3
1602386.14596411480846.1141741541602519.49504603481266.163782212
1602718.18517809481418.181735605
#Sta/Elev= 30
       0  657.55     4.4  655.97    11.3   651.6    28.5  650.53    76.7  642.91
   100.8  632.84   193.1  628.97     220   628.7   248.8  628.33     266  627.18
   279.8  624.93  304.76  624.17   313.3  623.37   345.2  624.16   378.6  623.44
   393.4  624.39   444.8  624.95     453  626.44   465.5   630.7     474  631.89
   551.3   634.9   560.8   637.7   581.7  654.16   589.4  658.67   597.7  661.09
   618.3  663.75   634.9  673.63   643.1  677.57   658.9  682.53   690.9  689.69
#Mann= 5 ,-1,0
       0     .06       0     220     .07       0  304.76    .045       0
   345.2     .07       0  540.71     .06       0
Bank Sta=304.76,345.2
XS Rating Curve= 0 ,0
Exp/Cntr(USF)=0,0
Exp/Cntr=0.3,0.1

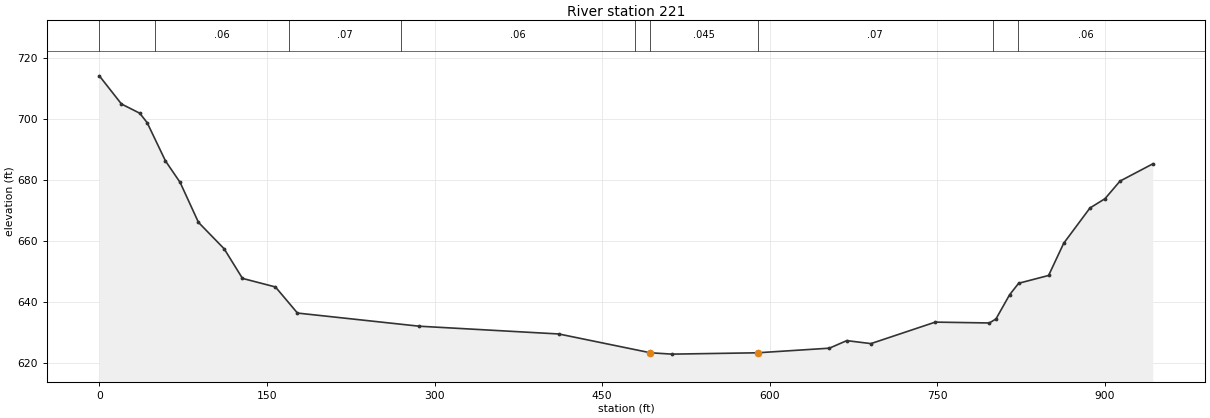
Type RM Length L Ch R = 1 ,221     ,,,
XS GIS Cut Line= 4
1602219.51550273480741.8731383421602221.03688514480921.396263302
1602558.78378125 481444.751814031602695.70819859481475.179462328
#Sta/Elev= 30
       0  714.09    19.8  704.85    36.2  701.82    42.8  698.72    59.2  686.17
    72.3  679.13    88.7  666.03   111.7  657.36   128.1  647.65   157.6  644.84
   177.3  636.28   286.2  631.97   411.2  629.42   493.2  623.25   512.5  622.81
     589623.2462   653.3  624.76   668.9  627.24   690.5  626.26   748.1  633.31
   796.5  633.03   802.4  634.35   814.6  642.28   822.7  646.05   849.5  648.61
     863  659.16   886.5  670.74     900   673.8   913.4  679.56   942.7  685.21
#Mann= 9 ,-1,0
       0      .1       0      50     .06       0     170     .07       0
  269.53     .06       0  479.53    .025       0   493.2    .045       0
     589     .07       0  799.53    .025       0  822.41     .06       0
Bank Sta=493.2,589
XS Rating Curve= 0 ,0
Exp/Cntr(USF)=0,0
Exp/Cntr=0.3,0.1
LCMann Table=0

Chan Stop Cuts=-1
Use User Specified Reach Order=0
Composite Channel Slope=5